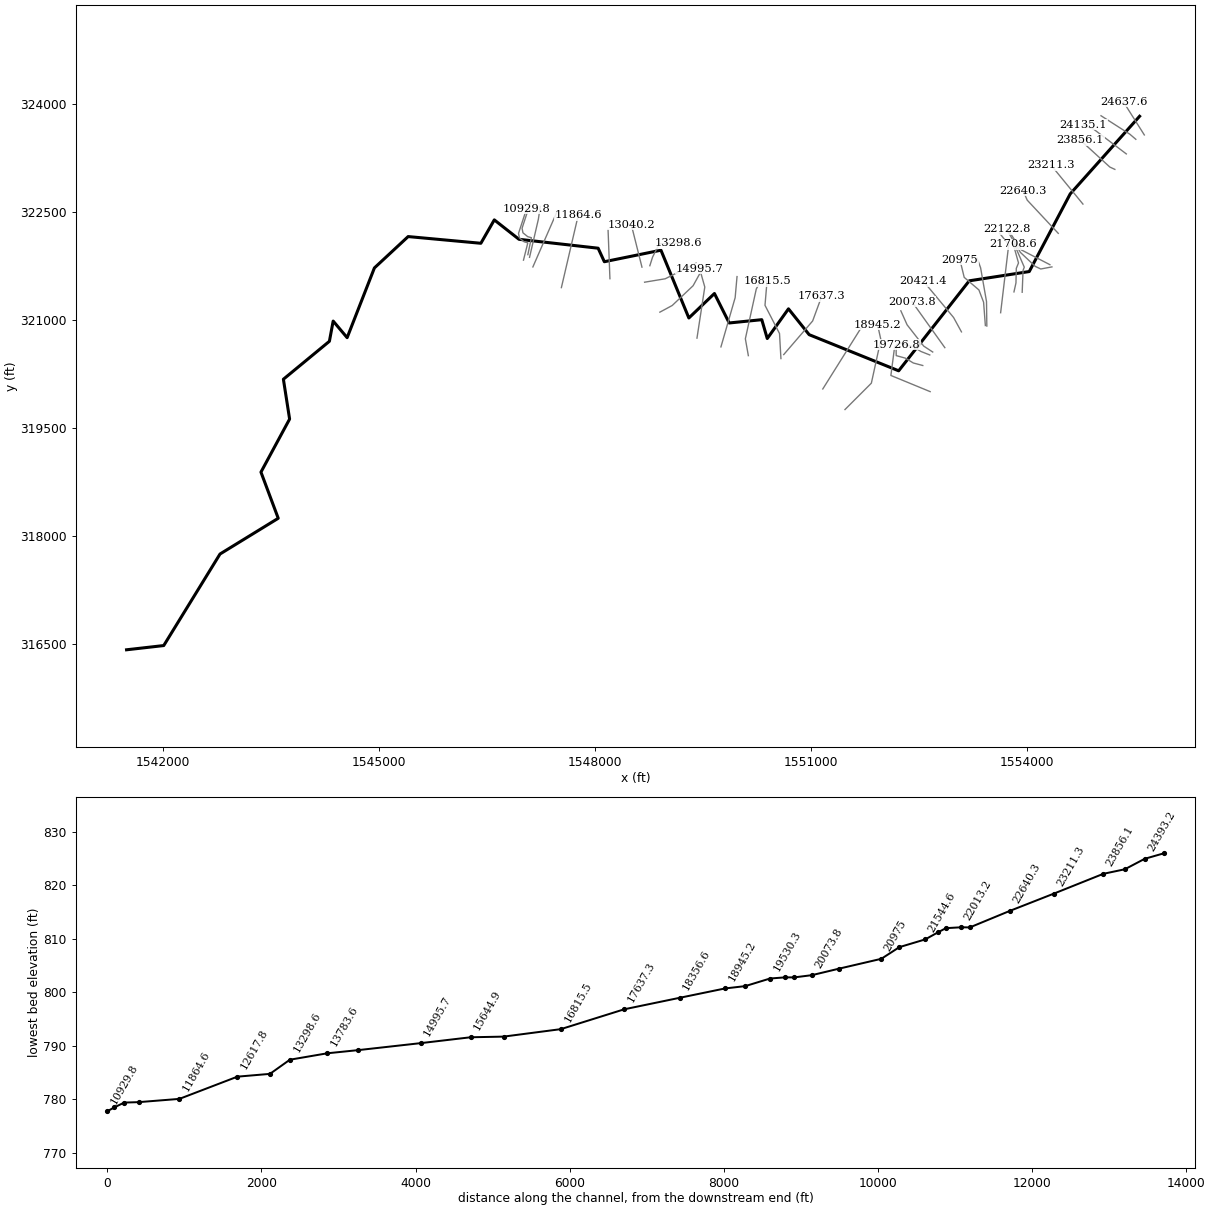
--- MCKIMCRK.prj (project) ---

Proj Title=MCKIMCRK
Current Plan=p01
Default Exp/Contr=0,0
English Units
Geom File=g01
Flow File=f01
Plan File=p01
BEGIN DESCRIPTION:
END DESCRIPTION:
DSS Export Rating Curves= 0
DSS Export Rating Curve Sorted= 0
DSS Export Volume Flow Curves= 0
DXF OffsetX= 0
DXF OffsetY= 0
DXF ScaleX= 0
DXF ScaleY= 0

--- MCKIMCRK.p01 (plan) ---

Plan Title=Floodplain
Program Version=4.00
Geom File=g01
Flow File=f01
K Sum by GR=0
Std Step Tol=0.01
Critical Tol=0.01
Num of Std Step Trials=20
Max Error Tol=0.3
Flow Tol Ratio=0.001
Split Flow NTrial=30
Split Flow Tol=0.02
Split Flow Ratio=0.02
Log Output Level=0
Friction Slope Method=1
Unsteady Friction Slope Method=2
Unsteady Bridges Friction Slope Method=1
Global Log Level=0
CheckData=False
Run HTab=0
Run UNet=0
Run PostProcess=0
UNET Theta=0
UNET Theta Warmup=0
UNET ZTol=0
UNET ZSATol=0
UNET MxIter=0
UNET MaxInSteps=0
UNET DtIC=0
UNET DtMin=0
UNET MaxCRTS=0
UNET WFStab=0
UNET SFStab=0
UNET WFX=0
UNET SFX=0
UNET DSS MLevel=0
UNET DZMax Abort=0
UNET Convert EG Bridges=0
UNET Use Existing IB Tables=0
UNET Froude Limit=0
UNET Froude Power=0
Write IC File=0
Echo Input=False
Echo Output=False
Write Detailed=0

--- MCKIMCRK.f01 (steady flow) ---

Flow Title=NFF Regression Equation
Program Version=4.10
Number of Profiles= 1
Profile Names=P100yr
River Rch & RM=MCKIMCRK,Main            ,24637.6
 1236.97
River Rch & RM=MCKIMCRK,Main            ,22640.3
1271.252
River Rch & RM=MCKIMCRK,Main            ,18356.6
1409.295
River Rch & RM=MCKIMCRK,Main            ,17637.3
1988.234
River Rch & RM=MCKIMCRK,Main            ,13040.2
2160.531
River Rch & RM=MCKIMCRK,Main            ,9231.3
2300.648
River Rch & RM=MCKIMCRK,Main            ,8386.3
2493.354
River Rch & RM=MCKIMCRK,Main            ,1296.3
2607.914
Boundary for River Rch & Prof#=MCKIMCRK,Main            , 1
Up Type= 0
Dn Type= 3
Dn Slope=0.0005
DSS Import GetInterval= 0
DSS Import GetPeak= 0
DSS Import FillOption= 0

--- MCKIMCRK.g01 (geometry) ---

Geom Title=USGS 10m DEM
Program Version=4.10

River Reach=MCKIMCRK        ,Main
Reach XY= 30
     1555559.966      323826.461     1554596.168      322748.338
      1554027.31      321670.183     1553193.521      321541.352
     1552213.517      320291.777     1550970.027      320793.687
      1550682.97      321152.396     1550388.239      320739.902
     1550312.073      321001.646     1549859.599      320956.074
     1549654.521      321365.145     1549299.226      321025.156
     1548911.654      321966.505      1548125.49      321806.436
     1548039.119      321994.283     1546939.778      322117.893
     1546596.897      322387.512      1546410.35        322062.7
     1545400.195      322155.827     1544931.509      321720.256
     1544552.771       320751.95      1544358.76      320982.419
     1544306.442      320701.713     1543667.435      320174.658
      1543753.65      319621.567     1543355.733      318884.892
     1543595.751       318243.79     1542787.046      317747.557
     1542005.362      316476.333     1541488.944      316417.618

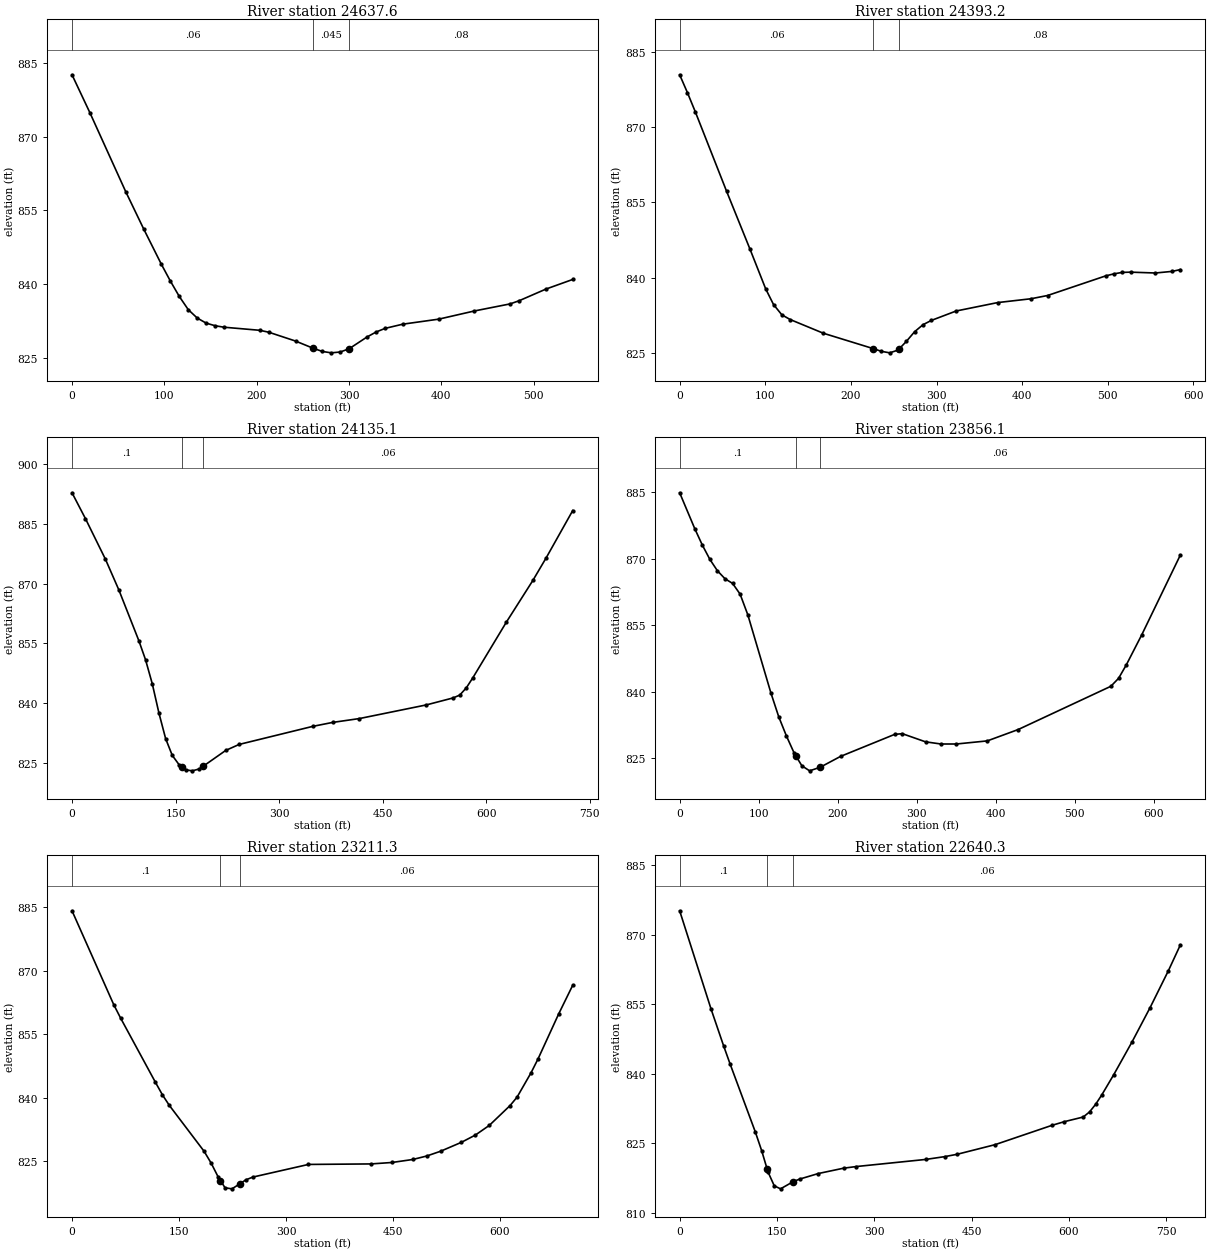
Type RM Length L Ch R = 1 ,24637.6 ,237.6,244.4,251.7
XS GIS Cut Line= 2
     1555625.552      323567.275     1555335.621      324025.608
#Sta/Elev= 30
       0  882.64    19.4   874.9    58.1  858.86    77.5  851.28    96.8  844.03
   106.5  840.63   116.2  837.48   125.9   834.8   135.6  833.09   145.3  832.05
     155  831.52   164.6  831.22   203.4  830.59   213.1   830.2   242.1   828.4
   261.5  826.91   271.2  826.28   280.8     826   290.5  826.17   300.2  826.84
   319.6  829.24   329.3  830.24     339  830.98   358.3  831.84   397.1  832.86
   435.8  834.53   474.5  835.97   484.2  836.61   513.3  838.99   542.3  840.95
#Mann= 3 , 0 , 0
       0     .06       0   261.5    .045       0   300.2     .08       0
Bank Sta=261.5,300.2
XS Rating Curve= 0 ,0
Exp/Cntr=0.3,0.1

Type RM Length L Ch R = 1 ,24393.2 ,260.6,258.2,255.5
XS GIS Cut Line= 3
     1555507.496      323506.511     1555424.163      323577.692
      1555023.99      323833.768
#Sta/Elev= 30
       0  880.47     9.1   876.9    18.3  873.07    54.8  857.23    82.2  845.65
   100.5  837.74   109.6  834.63   119.3  832.58     129  831.64   167.8   828.9
   225.9  825.84   235.6  825.29   245.3  824.99     255  825.54  256.27825.7665
   264.7  827.27   274.4  829.21   284.1   830.6   293.8  831.45   322.9  833.34
   371.4  835.02   410.2  835.78   429.6  836.43   497.4  840.34   507.1  840.75
   516.8  841.04   526.5  841.09   555.6  840.92     575  841.24   584.7   841.6
#Mann= 3 , 0 , 0
       0     .06       0   225.9    .045       0  256.27     .08       0
Bank Sta=225.9,256.27
XS Rating Curve= 0 ,0
Exp/Cntr=0.3,0.1

Type RM Length L Ch R = 1 ,24135.1 ,280.3,279,277.4
XS GIS Cut Line= 3
     1555375.273      323303.687     1554927.635      323642.796
     1554777.462        323707.9
#Sta/Elev= 30
       0  892.84    19.4  886.37    48.4  876.16    67.8  868.47    96.8  855.71
   106.5  850.92   116.2  844.93   125.9  837.54   135.6  831.12   145.2  826.92
   154.9  824.61  159.46823.9847   164.6  823.28   174.3  823.03     184  823.49
  190.34 824.223   222.7  828.16   242.1  829.66   348.6  834.19   377.6  835.19
   416.4  836.16   513.2  839.58   551.9  841.33   561.6  842.04   571.2  843.88
   580.8  846.45     629  860.32   667.5  870.82   686.8   876.5   725.3  888.38
#Mann= 3 , 0 , 0
       0      .1       0  159.46    .045       0  190.34     .06       0
Bank Sta=159.46,190.34
XS Rating Curve= 0 ,0
Exp/Cntr=0.3,0.1

Type RM Length L Ch R = 1 ,23856.1 ,648,644.8,641.2
XS GIS Cut Line= 3
     1555216.264      323088.976     1555146.819      323121.095
     1554735.361      323496.963
#Sta/Elev= 30
       0  884.86    19.1  876.78    28.7  873.07    38.3  869.83    47.8  867.28
    57.4  865.48      67  864.43    76.5  862.02    86.3  857.34   115.6  839.68
   125.4  834.37   135.2  830.02     145  826.16   146.9825.6054   154.7  823.32
   164.5  822.18   178.1823.0078   203.6  825.43     272  830.39   281.8  830.56
   311.2  828.72   330.7  828.23   350.3  828.23   389.4  828.93   428.5  831.49
   545.8  841.24   555.6  843.04   565.4  846.08   584.9  852.84   633.8  870.84
#Mann= 3 , 0 , 0
       0      .1       0   146.9    .045       0   178.1     .06       0
Bank Sta=146.9,178.1
XS Rating Curve= 0 ,0
Exp/Cntr=0.3,0.1

Type RM Length L Ch R = 1 ,23211.3 ,569.4,571,572.3
XS GIS Cut Line= 2
     1554773.035      322606.945     1554327.896      323150.001
#Sta/Elev= 30
       0   884.2    58.5  862.01    68.3  858.78     117  843.64   126.8  840.68
   136.5  838.18   185.3  827.32     195  824.58   204.8  821.32  208.23820.4081
   214.6  818.71   224.3  818.46  235.99819.7124   243.8  820.59   253.6  821.24
   331.6  824.23   419.4  824.35   448.6  824.69   477.9   825.4   497.4  826.22
   516.9  827.35   546.1  829.46   565.6  831.17   585.2  833.46   614.4  838.16
   624.2  840.16   643.7  845.89   653.4  849.13   682.7  859.89   702.2   866.6
#Mann= 3 , 0 , 0
       0      .1       0  208.23    .045       0  235.99     .06       0
Bank Sta=208.23,235.99
XS Rating Curve= 0 ,0
Exp/Cntr=0.3,0.1

Type RM Length L Ch R = 1 ,22640.3 ,509.6,517.5,525.1
XS GIS Cut Line= 3
     1554430.098      322200.727     1553998.559      322662.128
     1553943.004        322790.6
#Sta/Elev= 30
       0  875.12    48.6  853.87      68  845.93    77.8   842.1   116.6  827.49
   126.4  823.45  134.67819.5623   136.1  818.89   145.8  815.88   155.5  815.23
     175  816.78   184.7  817.32   213.8  818.53   252.7  819.68   272.1  820.03
     379  821.56   408.2  822.16   427.6  822.67     486  824.74   573.4  828.89
   592.9   829.7     622   830.7   631.8  831.81   641.1  833.44   650.4  835.42
   669.1  839.84   697.1  846.85   725.1  854.28   753.1  862.18   771.7  867.78
#Mann= 3 , 0 , 0
       0      .1       0  134.67    .045       0     175     .06       0
Bank Sta=134.67,175
XS Rating Curve= 0 ,0
Exp/Cntr=0.3,0.1

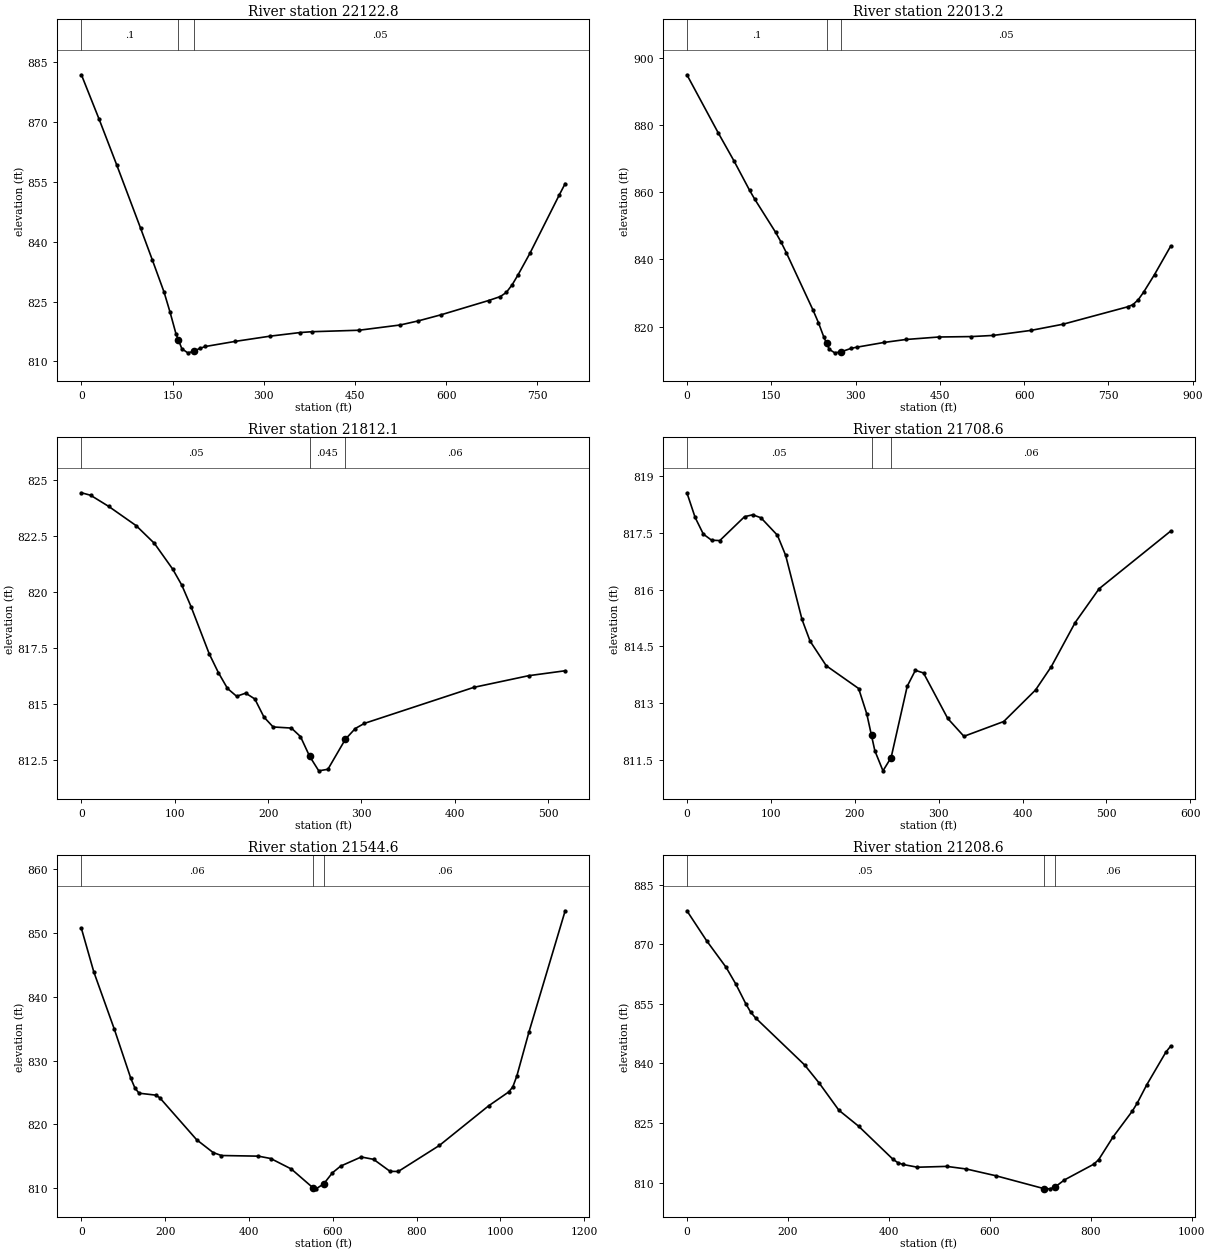
Type RM Length L Ch R = 1 ,22122.8 ,115.4,109.6,103.3
XS GIS Cut Line= 3
     1554313.928      321765.422     1553917.068       321971.05
     1553724.189      322261.491
#Sta/Elev= 30
       0  881.78    29.2  870.62    58.3  859.11    97.2  843.41   116.6  835.43
     136  827.32   145.8  822.32   155.5  816.92   159.6815.3349   165.2  813.17
   174.9  812.15   184.6  812.53   194.3  813.24     204  813.74   252.6  815.01
   310.9  816.34   359.5  817.23     379  817.44   456.6  817.81   524.4  819.13
   553.5  820.13   592.2  821.71   669.7  825.25   689.1  826.25   698.8  827.28
   708.5  829.21   718.1  831.68   737.5  837.04   785.9  851.69   795.6  854.53
#Mann= 3 , 0 , 0
       0      .1       0   159.6    .045       0   184.6     .05       0
Bank Sta=159.6,184.6
XS Rating Curve= 0 ,0
Exp/Cntr=0.3,0.1

Type RM Length L Ch R = 1 ,22013.2 ,224.8,201,179.3
XS GIS Cut Line= 5
     1554342.264      321734.733     1554187.056      321705.567
     1554109.777      321742.408     1553904.486      321936.103
     1553731.809      322223.066
#Sta/Elev= 30
       0  894.92    55.7  877.64    83.6  869.34   111.5  860.55   120.8  857.87
   157.9  848.02   167.4  845.18     177  841.93   224.5  824.86     234  821.17
   243.5  816.93   248.5815.0422   253.3  813.23     263  812.18   274.5 812.498
   292.2  813.51   301.9  813.85   350.6  815.27   389.5  816.15   447.9  816.89
   506.3  817.02   544.9  817.36   611.9  818.85   669.3   820.7   784.1  825.87
   793.7  826.53   803.3  828.04   812.8  830.29     832  835.48   860.7  843.92
#Mann= 3 , 0 , 0
       0      .1       0   248.5    .045       0   274.5     .05       0
Bank Sta=248.5,274.5
XS Rating Curve= 0 ,0
Exp/Cntr=0.3,0.1

Type RM Length L Ch R = 1 ,21812.1 ,98.8,103.5,104.7
XS GIS Cut Line= 4
     1553929.086      321382.686     1553941.238      321685.637
     1553958.188      321730.798     1553814.166      322062.367
#Sta/Elev= 27
       0  824.43     9.8  824.32    29.3  823.82    58.7  822.96    78.2  822.17
    97.8  821.02   107.6   820.3   117.4  819.35   136.9  817.24   146.7   816.4
   156.5  815.69   166.3  815.34     176  815.48   185.8  815.22   195.6  814.41
   205.4  813.97     225  813.92   234.7  813.54   244.5  812.66   254.3  812.01
   264.1  812.08   282.8  813.42   293.4   813.9   303.2  814.13   420.5  815.74
   479.2  816.26   518.3  816.48
#Mann= 3 , 0 , 0
       0     .05       0   244.5    .045       0   282.8     .06       0
Bank Sta=244.5,282.8
XS Rating Curve= 0 ,0
Exp/Cntr=0.3,0.1

Type RM Length L Ch R = 1 ,21708.6 ,166.2,164,161.1
XS GIS Cut Line= 5
     1553814.936       321387.46     1553842.714      321511.939
     1553847.402      321714.544     1553878.035      321789.593
     1553805.485      322048.478
#Sta/Elev= 30
       0  818.55     9.8   817.9    19.6  817.46    29.4   817.3    39.2  817.29
    68.7  817.92    78.5  817.97    88.3  817.89   107.9  817.43   117.7   816.9
   137.2  815.21   146.8  814.64   166.1  813.99   204.7  813.39   214.4  812.72
  220.02812.1522     224  811.75   233.7  811.22   243.4  811.57   262.6  813.45
   272.3  813.87     282   813.8   310.9   812.6   330.2  812.13   377.6  812.52
   415.5  813.35   434.4  813.97   462.8  815.13   491.3  816.02   576.6  817.54
#Mann= 3 , 0 , 0
       0     .05       0  220.02    .045       0   243.4     .06       0
Bank Sta=220.02,243.4
XS Rating Curve= 0 ,0
Exp/Cntr=0.3,0.1

Type RM Length L Ch R = 1 ,21544.6 ,328.5,336,342.1
XS GIS Cut Line= 3
     1553629.757      321098.288     1553742.229      322044.139
     1553615.644      322201.342
#Sta/Elev= 30
       0  850.69    29.5   843.9    78.6   834.9   117.8  827.23   127.7   825.7
   137.5  824.89   176.8  824.59   186.6   824.2     275   817.6   314.2   815.6
   333.9  815.13   422.2  815.03   451.7  814.66   500.8  813.02     552810.1064
   559.7  809.91     578810.6692     599  812.42   618.6  813.47   667.7   814.9
   697.2  814.53   736.5  812.65   756.1  812.63   854.3  816.71   971.7  822.91
  1019.8  825.09  1029.4  825.87    1039  827.57  1067.8  834.43  1154.4  853.46
#Mann= 3 , 0 , 0
       0     .06       0     552    .045       0     578     .06       0
Bank Sta=552,578
XS Rating Curve= 0 ,0
Exp/Cntr=0.3,0.1

Type RM Length L Ch R = 1 ,21208.6 ,214.6,233.7,248.8
XS GIS Cut Line= 4
     1553438.081      320913.467     1553433.625      321253.436
     1553351.594      321722.186     1553303.417      321856.301
#Sta/Elev= 30
       0  878.43    38.9  870.92    77.7  864.19    97.1  859.94   116.6  855.05
   126.3  852.93     136  851.47   233.1  839.65   262.3  835.04   301.1  828.24
     340  824.24     408  815.93   417.7  815.06   427.4  814.61   456.5   813.9
   514.8  814.11   553.7  813.45   611.9  811.76  706.57808.5375   718.8  808.46
   728.9808.8768   747.9   810.7   806.2  814.67   815.9  815.83   844.4  821.54
   882.4  828.02   891.9  829.97   910.9  834.61   948.9  842.86   958.4  844.36
#Mann= 3 , 0 , 0
       0     .05       0  706.57    .045       0   728.9     .06       0
Bank Sta=706.57,728.9
XS Rating Curve= 0 ,0
Exp/Cntr=0.3,0.1

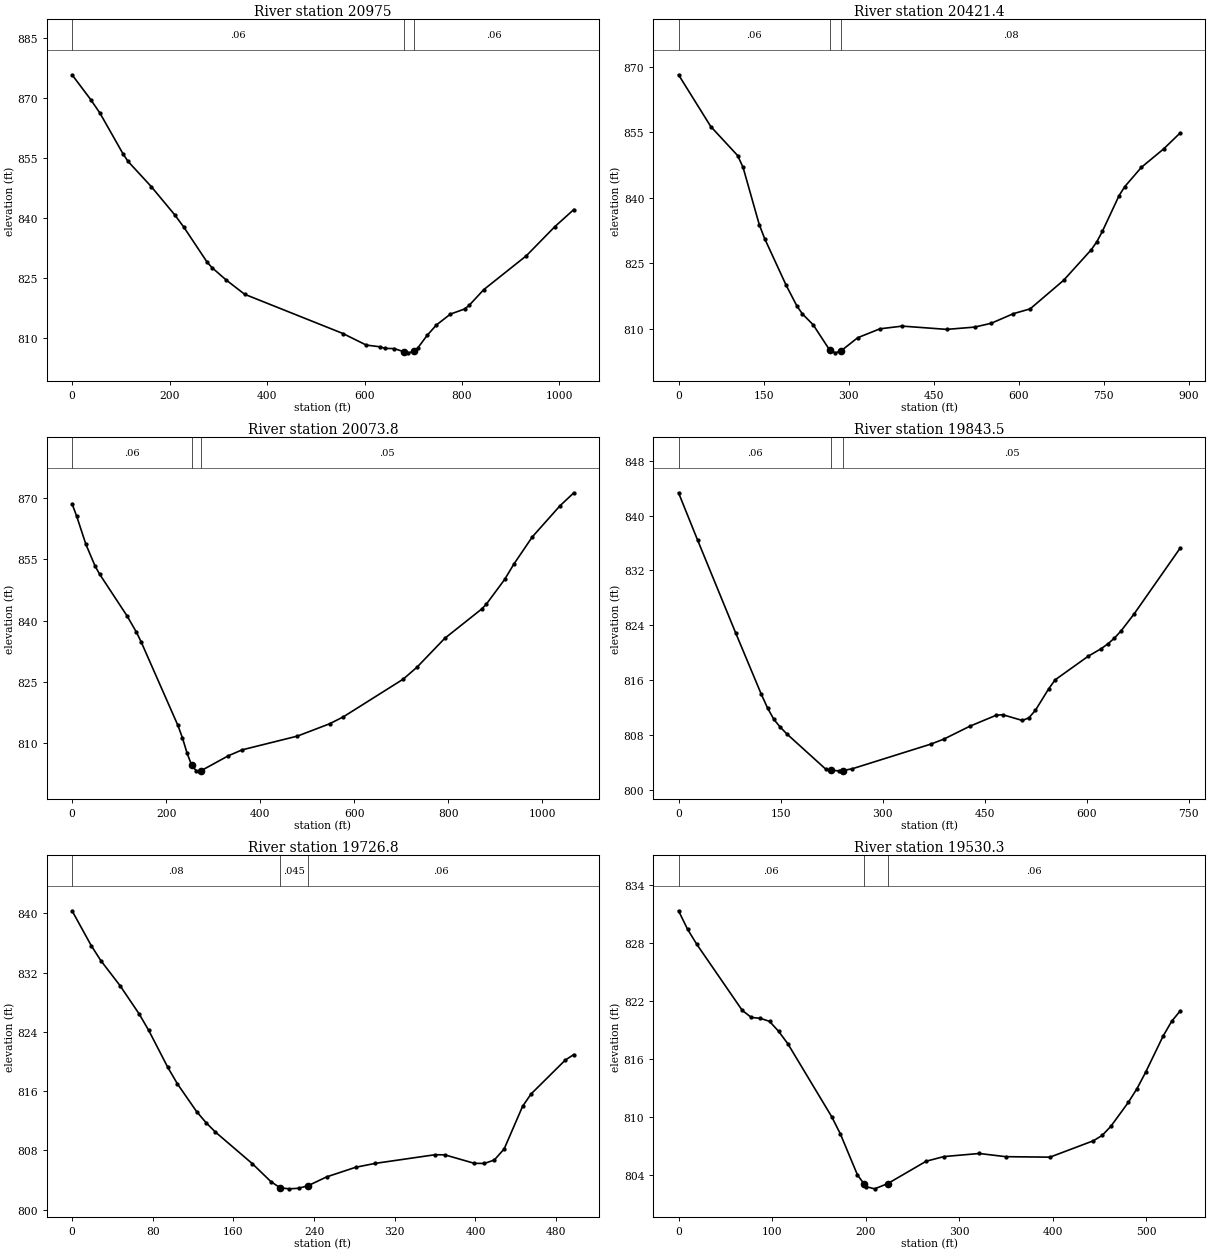
Type RM Length L Ch R = 1 ,20975   ,557.6,553.6,549.3
XS GIS Cut Line= 5
     1553417.737      320920.227     1553392.997      321244.446
     1553327.893      321415.019     1553123.729      321589.374
     1553063.833      321835.467
#Sta/Elev= 30
       0  875.77    38.2  869.58    57.4  866.15   105.2  855.87   114.8  854.13
   162.6  847.81   210.4   840.8   229.5  837.66   277.3   828.9   286.9   827.6
   315.6  824.54     354  820.92   555.7  811.11   603.6  808.22   632.4  807.78
     642  807.39   661.2  807.34   680.3  806.56   689.9  806.28   700.8806.6593
   709.1  807.46   728.3  810.62   747.4  813.23   776.2  815.96   805.4  817.24
   815.2  818.21   844.4  822.05   932.1  830.55   990.5  837.82  1029.5   842.1
#Mann= 3 , 0 , 0
       0     .06       0   680.3    .045       0   700.8     .06       0
Bank Sta=680.3,700.8
XS Rating Curve= 0 ,0
Exp/Cntr=0.3,0.1

Type RM Length L Ch R = 1 ,20421.4 ,349,347.6,345.8
XS GIS Cut Line= 3
     1553085.535      320832.429      1552976.16      321032.082
     1552556.021       321537.29
#Sta/Elev= 30
       0  868.19    56.9  856.31   104.3  849.65   113.8  846.94   142.3  833.84
   151.8  830.63   189.7  819.93   208.7  815.16   218.2  813.38   237.5  810.83
   266.9  804.97   276.7  804.42     287804.9225   315.9  807.89   355.1  809.93
   394.4  810.55   472.8   809.8   521.9  810.32   551.3   811.2   590.5  813.41
   619.9   814.5   678.8  821.04   727.8  828.08   737.6  829.92   747.4  832.32
   776.8   840.5   786.7  842.53   816.1  846.97   855.3  851.19   884.7  854.88
#Mann= 3 , 0 , 0
       0     .06       0   266.9    .045       0     287     .08       0
Bank Sta=266.9,287
XS Rating Curve= 0 ,0
Exp/Cntr=0.3,0.1

Type RM Length L Ch R = 1 ,20073.8 ,229.3,230.3,231.2
XS GIS Cut Line= 2
     1552854.849      320613.245     1552399.749      321249.481
#Sta/Elev= 30
       0  868.63     9.8  865.58    29.3  858.72    48.9  853.38    58.7  851.36
   117.3  841.09   136.9  837.16   146.7  834.84   224.9  814.37   234.7  811.27
   244.4  807.58   254.2   804.6     264  803.23   273.6803.2202   273.8  803.22
   332.5  806.93   361.8  808.37   479.1  811.73   547.6  814.75   576.9  816.46
     704  825.68   733.4  828.62   792.1  835.66   870.5  842.83   880.3  843.99
   919.6   850.1   939.2  853.86   978.4  860.52  1037.2  868.14  1066.7  871.32
#Mann= 3 , 0 , 0
       0     .06       0   254.2    .045       0   273.6     .05       0
Bank Sta=254.2,273.6
XS Rating Curve= 0 ,0
Exp/Cntr=0.3,0.1

Type RM Length L Ch R = 1 ,19843.5 ,108.6,116.7,124.9
XS GIS Cut Line= 4
     1552686.448       320552.76     1552561.448      320634.704
     1552330.545      320930.364      1552243.74      321124.809
#Sta/Elev= 30
       0  843.32      28  836.43    84.1  822.87   121.4  814.02   130.8  811.97
   140.1   810.3   149.5  809.17   159.1  808.19   216.8  803.01   223.5802.8774
     236   802.8   241.5802.8386   255.3   803.1   370.7  806.69   389.9  807.42
   428.4  809.31   466.9   810.9   476.5  810.98   505.4  810.14     515  810.53
   524.6  811.62     544  814.74   553.6  816.06     602  819.49   621.4  820.61
   631.1   821.3   640.8  822.15   650.4  823.18   669.8  825.68   737.6  835.29
#Mann= 3 , 0 , 0
       0     .06       0   223.5    .045       0   241.5     .05       0
Bank Sta=223.5,241.5
XS Rating Curve= 0 ,0
Exp/Cntr=0.3,0.1

Type RM Length L Ch R = 1 ,19726.8 ,196.3,196.5,196.3
XS GIS Cut Line= 5
     1552645.396      320511.841     1552521.687      320560.652
     1552411.926      320627.626     1552241.653      320675.033
       1552185.5      320656.112
#Sta/Elev= 30
       0  840.34      19  835.64    28.5  833.62    47.5  830.25    66.5  826.42
      76   824.2      95  819.19   104.5  816.97   123.5  813.24     133  811.72
   142.2  810.47   178.9  806.19   197.3  803.77   206.5  802.94   215.6  802.81
   224.8  802.89     234  803.23   252.4  804.42   281.2  805.72   300.8  806.25
   359.8  807.41   369.6   807.4     399  806.25   408.9  806.24   418.7   806.7
   428.5   808.2   446.8  813.96   455.2  815.62   489.1  820.19   497.6  820.94
#Mann= 3 , 0 , 0
       0     .08       0   206.5    .045       0     234     .06       0
Bank Sta=206.5,234
XS Rating Curve= 0 ,0
Exp/Cntr=0.3,0.1

Type RM Length L Ch R = 1 ,19530.3 ,349.1,321.7,290.7
XS GIS Cut Line= 5
     1552548.217      320365.411     1552416.582      320400.411
     1552306.821      320467.386     1552179.378      320502.868
     1552177.557      320642.321
#Sta/Elev= 30
       0  831.38     9.7  829.46    19.5  827.91    68.1  821.07    77.8  820.34
    87.6  820.24    97.3  819.93     107   818.9   116.8  817.62   163.8  810.05
     173  808.28   191.3  804.03   198.2  803.12   200.5  802.82   209.7  802.59
  223.74803.1366   264.8  805.45   283.7  805.93   321.5  806.25   349.8  805.92
   397.1  805.87   443.6  807.57   452.9  808.12   462.2  809.06   480.8  811.53
   490.1  812.95   499.4  814.66     518  818.39   527.2  819.93   536.5  821.03
#Mann= 3 , 0 , 0
       0     .06       0   198.2    .045       0  223.74     .06       0
Bank Sta=198.2,223.74
XS Rating Curve= 0 ,0
Exp/Cntr=0.3,0.1

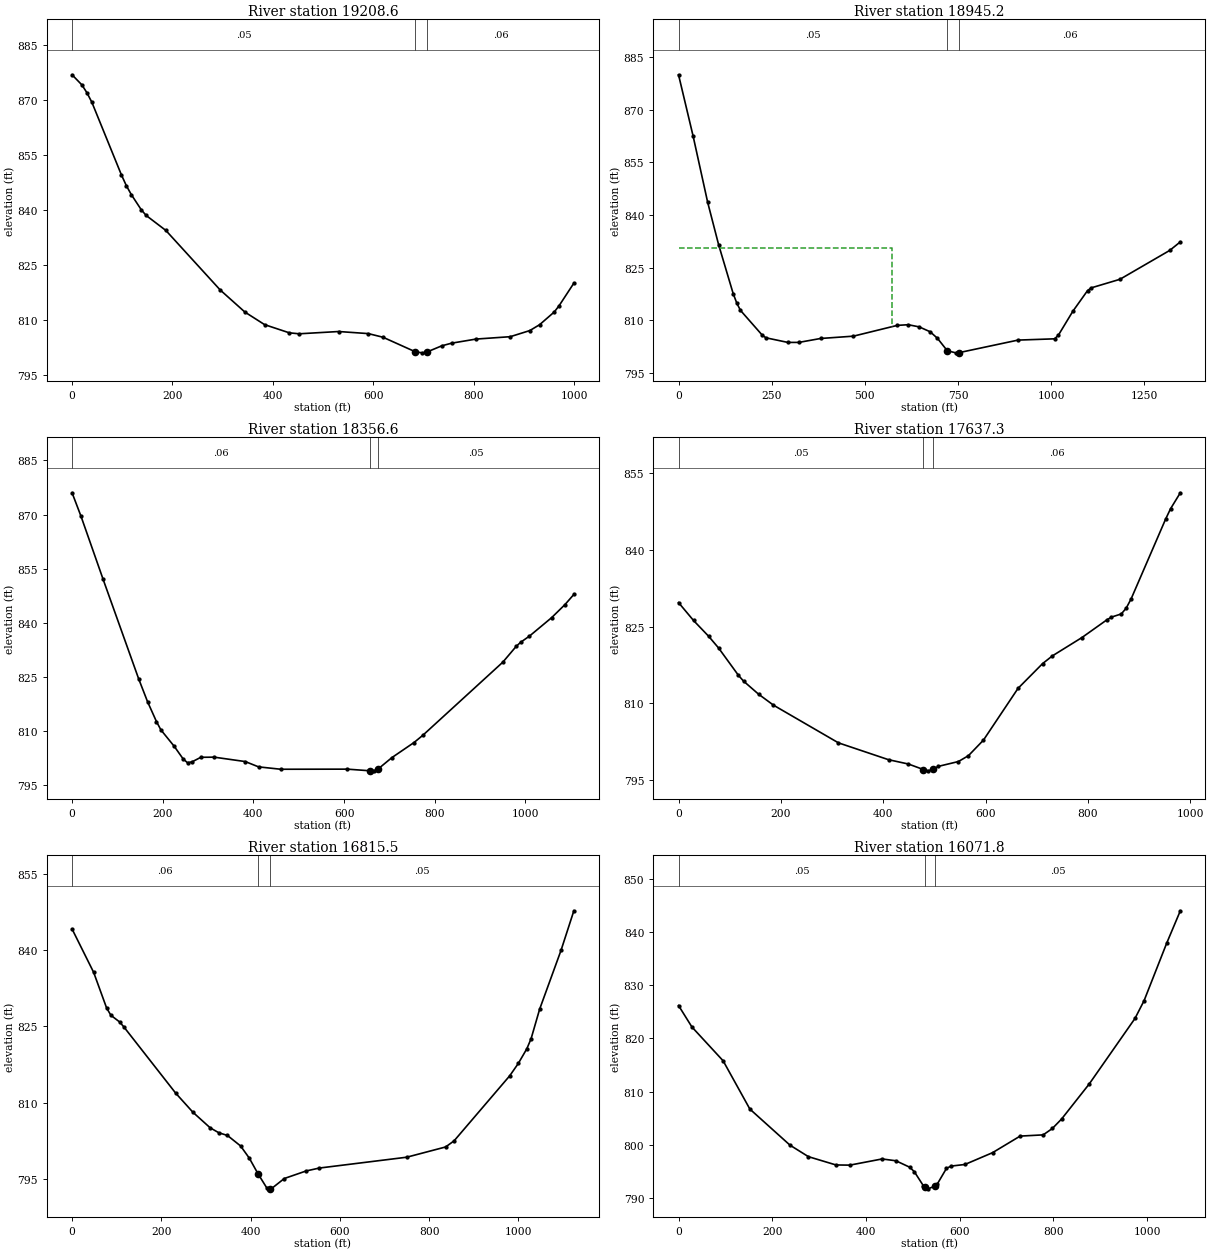
Type RM Length L Ch R = 1 ,19208.6 ,264,263.4,259.3
XS GIS Cut Line= 3
     1552650.874      320002.524     1552105.301      320227.133
     1552158.469      320632.949
#Sta/Elev= 30
       0  876.94    19.7  874.16    29.5  872.06    39.3  869.49    98.3  849.65
   108.2  846.69     118  844.29   137.7  840.18   147.5  838.61   186.8  834.52
     295   818.3   344.2  812.28   383.5  808.85   432.7  806.62   452.3  806.36
     531  806.98     590  806.41   619.2  805.42   683.7  801.45   697.2  801.17
   706.9  801.41   736.2  803.08   755.7   803.8   804.4  804.92   872.6  805.57
   911.6  807.24   931.1  808.84   960.3  812.31     970  814.03   999.3  820.16
#Mann= 3 , 0 , 0
       0     .05       0   683.7    .045       0   706.9     .06       0
Bank Sta=683.7,706.9
XS Rating Curve= 0 ,0
Exp/Cntr=0.3,0.1

Type RM Length L Ch R = 1 ,18945.2 ,590.9,588.6,581.7
XS GIS Cut Line= 4
     1551467.843      319753.833     1551834.162      320120.152
     1551966.107      320724.319     1551920.968       320929.18
#Sta/Elev= 30
       0  879.92    39.1  862.46    78.2  843.58   107.5  831.54   146.6   817.6
   156.4  814.86   166.2  812.82   224.8  805.74   234.6  805.01   293.2   803.7
   322.6   803.7   381.2  804.82   469.2  805.48   586.8  808.55   616.2  808.74
   645.7  808.12   675.1  806.73   694.7  804.86     721  801.33   743.8  800.73
   753.6  800.81   910.7  804.36  1008.8  804.72  1018.7   805.7  1057.9  812.58
  1097.2  818.44    1107  819.23  1184.1  821.67  1317.6  829.89  1346.2  832.33
#Mann= 3 , 0 , 0
       0     .05       0     721    .045       0   753.6     .06       0
#XS Ineff= 2 , 0
          572.25  830.69
Permanent Ineff=
       F       F
Bank Sta=721,753.6
XS Rating Curve= 0 ,0
Exp/Cntr=0.3,0.1

Type RM Length L Ch R = 1 ,18356.6 ,719.6,719.3,713.7
XS GIS Cut Line= 2
     1551159.683       320039.77     1551747.791       320977.27
#Sta/Elev= 30
       0  876.03    19.6  869.56    68.6     852   146.9  824.47   166.5  818.13
   186.1  812.64   195.9  810.33   225.3  805.78   244.8  802.31   254.6  801.22
   264.4  801.46     284  802.73   313.4  802.77     382  801.55   411.3  800.08
   460.3  799.42   607.2  799.45   656.2     799     666  798.98   673.8  799.37
   705.2  802.63   754.1  806.82   773.7  808.84     950  829.09   979.4  833.45
   989.2  834.59  1008.8  836.32  1057.7  841.43  1087.1  845.05  1106.7  847.86
#Mann= 3 , 0 , 0
       0     .06       0   656.2    .045       0   673.8     .05       0
Bank Sta=656.2,673.8
XS Rating Curve= 0 ,0
Exp/Cntr=0.3,0.1

Type RM Length L Ch R = 1 ,17637.3 ,791.8,821.8,842.6
XS GIS Cut Line= 3
     1550617.148      320517.201     1551018.624       320983.78
     1551144.492      321326.662
#Sta/Elev= 30
       0  829.73    29.3  826.23    58.6  823.17    78.2  820.86   117.2  815.49
     127  814.38   156.3  811.83   185.6  809.67   312.6   802.3   410.4  799.01
   449.4  798.16   478.8  797.08   488.5  796.83   497.3  797.16   508.1  797.71
   547.1  798.65   566.7   799.8     596  802.84   663.6  812.96   711.6   817.8
   730.9  819.32   788.6   822.9   836.6  826.31   846.2  826.89   865.4  827.51
     875  828.64   884.7  830.47     952  846.04   961.6  848.06   980.8   851.2
#Mann= 3 , 0 , 0
       0     .05       0   478.8    .045       0   497.3     .06       0
Bank Sta=478.8,497.3
XS Rating Curve= 0 ,0
Exp/Cntr=0.3,0.1

Type RM Length L Ch R = 1 ,16815.5 ,755.2,743.7,733.2
XS GIS Cut Line= 4
     1550578.103      320461.606     1550558.572      320809.262
     1550356.749      321201.189     1550384.961       321535.39
#Sta/Elev= 30
       0  844.14    48.4  835.62    77.4  828.63      87   827.2   106.4   825.9
   116.1  824.91   232.1  811.92   270.8  808.16   309.5   805.1   328.9  804.13
   348.2   803.6   377.6  801.54   397.2  799.14   416.6796.0834   436.4  793.29
  442.73793.1779   446.2  793.12   475.6  795.15   524.5  796.63   553.9   797.2
   749.9  799.33     837  801.34   856.1  802.55   980.7  815.32   999.9  817.74
    1019  820.62  1028.6  822.61  1047.8  828.42  1095.7  839.96  1124.4  847.72
#Mann= 3 , 0 , 0
       0     .06       0   416.6    .045       0  442.73     .05       0
Bank Sta=416.6,442.73
XS Rating Curve= 0 ,0
Exp/Cntr=0.3,0.1

Type RM Length L Ch R = 1 ,16071.8 ,427.1,426.9,431.5
XS GIS Cut Line= 4
     1550125.495       320502.39     1550084.018      320736.726
     1550235.807      321427.679     1550294.766      321538.848
#Sta/Elev= 30
       0   826.2    28.6  822.16    95.2   815.8   152.3  806.72     238  799.93
   277.3  797.77   336.2  796.21   365.7  796.18   434.5  797.34     464     797
   493.4  795.79   503.3  794.95   522.9  792.27  526.38792.0742   532.7  791.72
  547.34792.2427   552.4  792.63     572  795.57   581.9     796   611.3   796.3
   670.3  798.52   729.2  801.64   778.4  801.87     798  803.07   817.7  804.85
   876.6  811.43   974.4  823.77   993.8  827.11  1042.2  837.95  1071.2  844.02
#Mann= 3 , 0 , 0
       0     .05       0  526.38    .045       0  547.34     .05       0
Bank Sta=526.38,547.34
XS Rating Curve= 0 ,0
Exp/Cntr=0.3,0.1

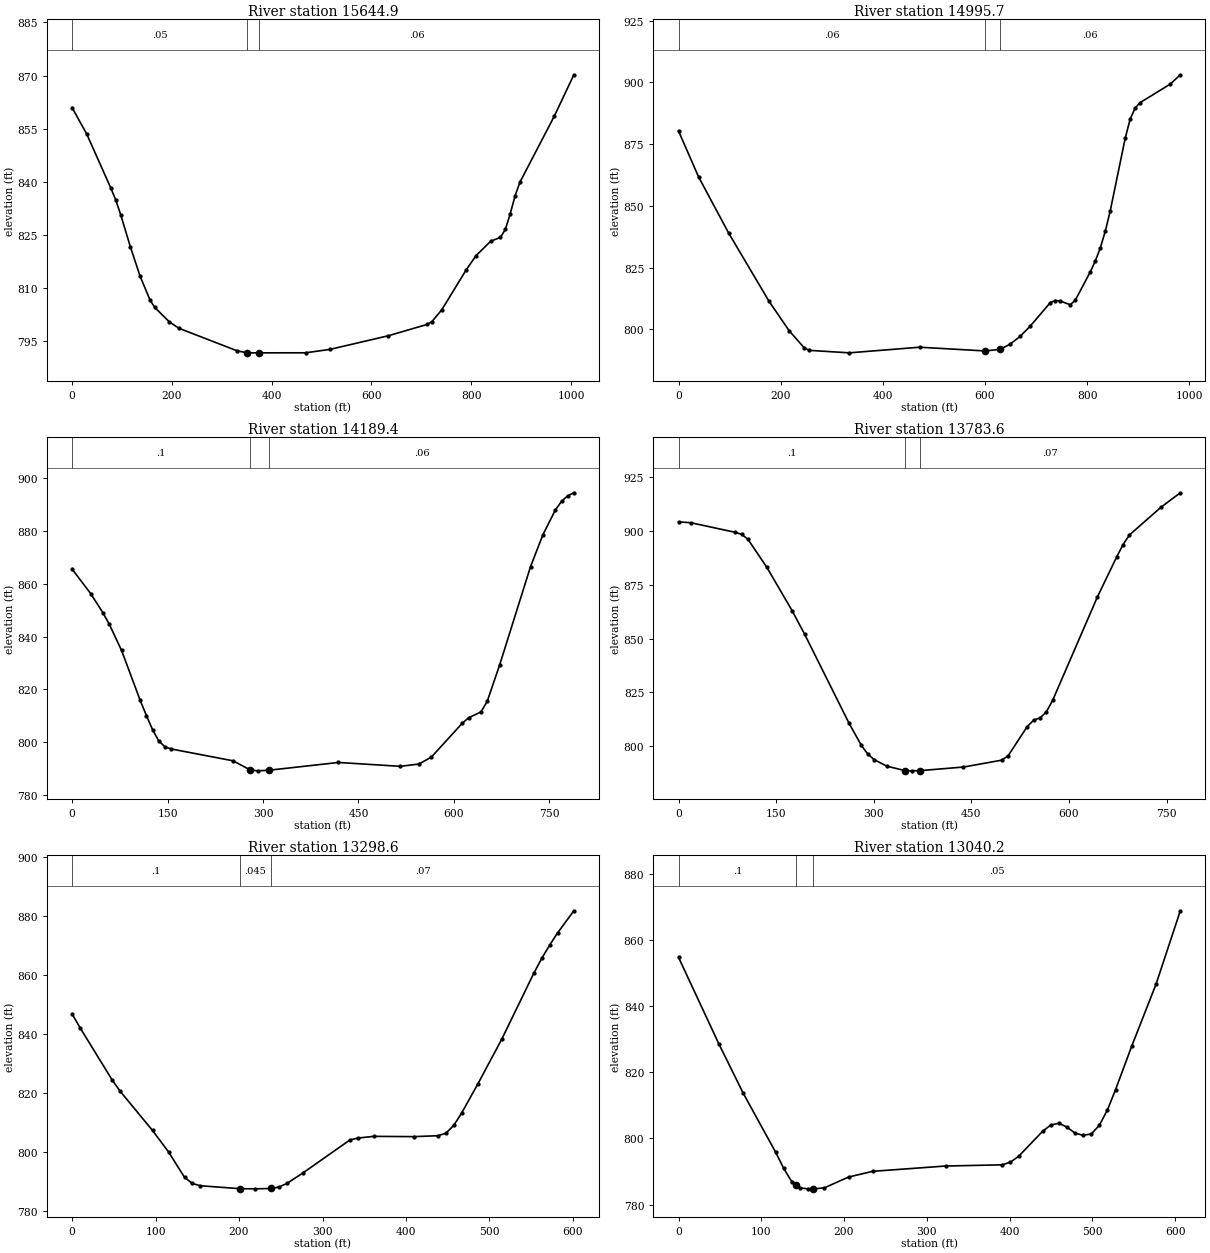
Type RM Length L Ch R = 1 ,15644.9 ,647.9,649.2,644.1
XS GIS Cut Line= 3
     1549744.753      320623.537     1549942.235      321307.131
     1549968.277        321600.1
#Sta/Elev= 30
       0  860.93    29.2  853.51      78  838.09    87.7  834.74    97.5  830.62
     117  821.51   136.5   813.2     156  806.61   165.7  804.44   194.9  800.36
   214.4  798.53   331.4  792.14   350.9   791.6  374.89   791.6   467.9  791.61
   516.6  792.57   633.6  796.42   711.6  799.63   721.4  800.45     741  803.77
     790  815.07   809.6  819.08     839  823.15   858.6  824.25   868.4  826.49
   878.2  830.94     888  836.03   897.8  839.91   966.4  858.48  1005.7  870.21
#Mann= 3 , 0 , 0
       0     .05       0   350.9    .045       0  374.89     .06       0
Bank Sta=350.9,374.89
XS Rating Curve= 0 ,0
Exp/Cntr=0.3,0.1

Type RM Length L Ch R = 1 ,14995.7 ,820.6,806.3,790
XS GIS Cut Line= 3
      1549412.07      320745.427     1549520.577      321455.062
     1549448.719      321709.599
#Sta/Elev= 30
       0  880.33    39.3  861.73    98.3  838.95     177  811.43   216.4   799.5
   245.8  792.58   255.7  791.51   334.4   790.5     472  792.78   599.9  791.27
   629.4   791.9     649  793.99   668.7  797.15   688.4  801.28   727.7  810.81
   737.5  811.68   747.3  811.49   766.9  809.98   776.7  811.79     806  823.24
   815.8  827.63   825.6   832.9   835.4  839.68   845.2  848.02   874.6  877.53
   884.4   885.3   894.2  889.74     904  891.89   962.8  899.36   982.4  903.12
#Mann= 3 , 0 , 0
       0     .06       0   599.9    .045       0   629.4     .06       0
Bank Sta=599.9,629.4
XS Rating Curve= 0 ,0
Exp/Cntr=0.3,0.1

Type RM Length L Ch R = 1 ,14189.4 ,410.7,405.8,398.5
XS GIS Cut Line= 4
     1548896.694      321106.188     1549067.969      321198.594
     1549358.065      321473.028     1549452.249      321643.297
#Sta/Elev= 30
       0  865.51    29.2  856.27    48.6  848.96    58.4  844.69    77.8  834.73
     107  815.89   116.8  810.12   126.5  804.77   136.2   800.5     146  798.28
   155.7  797.48     253  792.99     280 789.529     292   789.2   309.8 789.441
   418.6  792.37     516   790.9   545.2  791.79   564.7  794.42   613.4  807.27
   623.1  809.26   642.6   811.5   652.3  815.46   671.8  829.18   720.4  866.44
   739.9  878.52   759.3  887.81   769.1  891.13   778.8  893.25   788.5  894.38
#Mann= 3 , 0 , 0
       0      .1       0     280    .045       0   309.8     .06       0
Bank Sta=280,309.8
XS Rating Curve= 0 ,0
Exp/Cntr=0.3,0.1

Type RM Length L Ch R = 1 ,13783.6 ,524.9,485,495
XS GIS Cut Line= 3
     1548684.355      321522.227      1548971.17      321569.718
     1549399.773      321786.732
#Sta/Elev= 30
       0  904.25    19.4   903.8    87.2  899.37    96.9  898.44   106.6  896.17
   135.7  883.12   174.4  863.06   193.8  852.03   261.6  810.94     281  800.39
   290.7  796.43   300.5  793.82   320.1  790.77   348.4  788.67   359.4   788.6
  371.75788.7164   437.8  790.36   496.6  793.55   506.4  795.56   535.8  809.14
   545.6   812.1   555.4  813.18   565.2   815.9     575  821.42   643.7  869.38
   673.1  887.82   682.9  893.54   692.7   898.1   741.7  911.11   771.1  917.74
#Mann= 3 , 0 , 0
       0      .1       0   348.4    .045       0  371.75     .07       0
Bank Sta=348.4,371.75
XS Rating Curve= 0 ,0
Exp/Cntr=0.3,0.1

Type RM Length L Ch R = 1 ,13298.6 ,187.9,258.4,277.6
XS GIS Cut Line= 4
     1548757.195      321750.925     1548795.172      321870.282
     1548888.488      322055.829     1549156.556      322062.404
#Sta/Elev= 30
       0  846.78     9.6  842.08    48.2  824.29    57.8  820.47    96.4  807.21
   115.6  799.92   134.7  791.31   144.1  789.23   153.6  788.45   200.8  787.46
   219.7   787.4   238.5  787.52     248  788.03   257.4  789.24   276.3  792.74
   332.9  804.01   342.5  804.65   361.7  805.22   409.6  805.12   438.3  805.44
   447.9  806.29   457.4     809     467  813.31   486.2  823.07   514.9  838.32
   553.2  860.65   562.8  865.73   572.4  870.29   581.9  874.42   601.1  881.81
#Mann= 3 , 0 , 0
       0      .1       0   200.8    .045       0   238.5     .07       0
Bank Sta=200.8,238.5
XS Rating Curve= 0 ,0
Exp/Cntr=0.3,0.1

Type RM Length L Ch R = 1 ,13040.2 ,427.3,422.4,417.8
XS GIS Cut Line= 2
      1548647.82      321731.176      1548500.25      322319.284
#Sta/Elev= 30
       0  854.73    48.9  828.48    78.2  813.64   117.4  795.79   127.1  790.92
   136.9  786.88  142.07785.9003   146.7  785.02   156.5  784.75  162.11  784.75
     176  785.03   205.4  788.32   234.7  790.05   322.7  791.65   391.2  792.01
     401  792.83   410.8  794.55   440.1   802.2   449.9  804.05   459.6  804.58
   469.4   803.4   479.2  801.57     489  800.93   498.8  801.36   508.5  803.98
   518.3  808.65   528.1  814.78   547.7  827.97     577  846.66   606.3  868.82
#Mann= 3 , 0 , 0
       0      .1       0  142.07    .045       0  162.11     .05       0
Bank Sta=142.07,162.11
XS Rating Curve= 0 ,0
Exp/Cntr=0.3,0.1

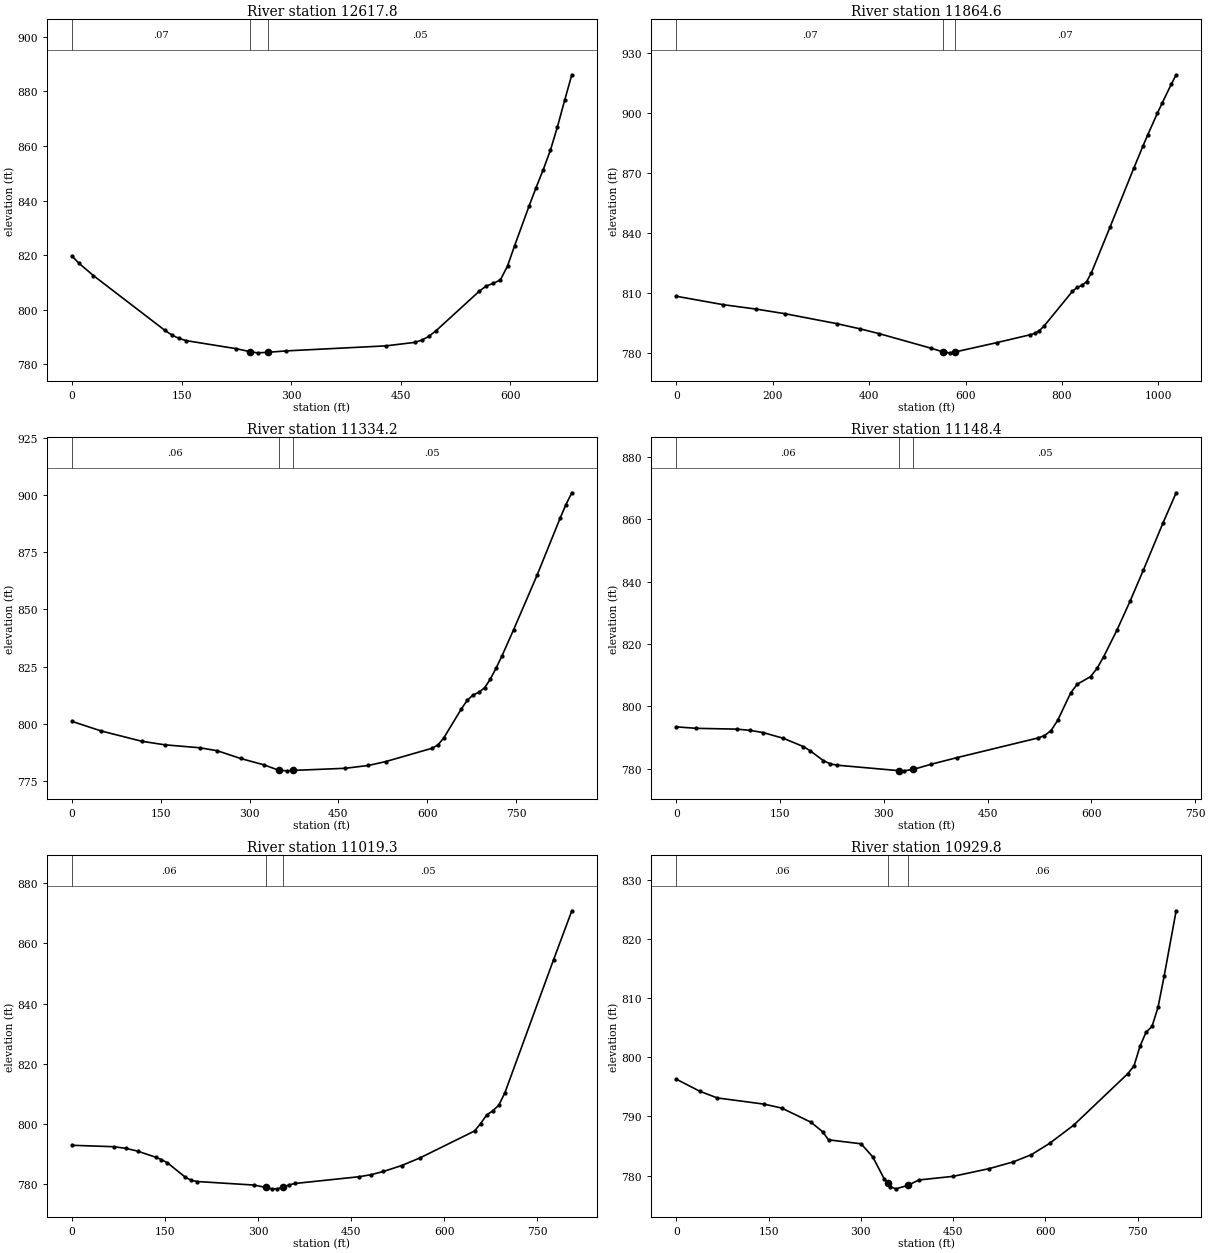
Type RM Length L Ch R = 1 ,12617.8 ,756.3,753.2,733.2
XS GIS Cut Line= 2
     1548202.941      321570.803       1548176.9      322254.397
#Sta/Elev= 30
       0  819.66     9.8  816.97    29.3  812.53     127  792.49   136.8  790.74
   146.6  789.49   156.4   788.7   224.8  785.75   244.3  784.61   254.1  784.23
  267.73784.4163   293.2  784.94     430  786.79   469.1  788.06   478.9  788.89
   488.6  790.29   498.4  792.35     557  806.69   566.8  808.68   576.6  809.65
   586.4  810.96   596.1  816.02   605.9  823.52   625.4  837.85   635.2  844.74
     645  851.31   654.8  858.42   664.5  867.06   674.3   876.7   684.1  886.04
#Mann= 3 , 0 , 0
       0     .07       0   244.3    .045       0  267.73     .05       0
Bank Sta=244.3,267.73
XS Rating Curve= 0 ,0
Exp/Cntr=0.3,0.1

Type RM Length L Ch R = 1 ,11864.6 ,532.9,530.4,526
XS GIS Cut Line= 2
     1547528.625      321446.834     1547763.868      322456.382
#Sta/Elev= 30
       0  808.36    97.8  804.13   166.2  801.92   224.9  799.66   332.5  794.68
   381.4  792.05   420.5  789.68   528.1   782.4  552.26780.6093   557.4  780.27
   567.2  780.07     577  780.45     665  785.19   733.4  789.09   743.2  789.79
     753  791.17   762.8  793.51   821.4  810.78   831.2  812.77     841  813.78
   850.8  815.62   860.6  819.97   899.7  843.05   948.6  872.29   968.1  883.66
   977.9  889.17   997.5  899.76  1007.3   904.8  1026.8  914.49  1036.6  919.09
#Mann= 3 , 0 , 0
       0     .07       0  552.26    .045       0     577     .07       0
Bank Sta=552.26,577
XS Rating Curve= 0 ,0
Exp/Cntr=0.3,0.1

Type RM Length L Ch R = 1 ,11334.2 ,181,185.8,189.1
XS GIS Cut Line= 2
     1547132.783      321734.224     1547470.795      322507.869
#Sta/Elev= 30
       0  801.08    49.1  796.91   117.8  792.39   157.1  790.83     216  789.54
   245.4  788.25   284.7  784.87     324   782.1     349  779.75   363.2  779.46
     373  779.64   461.4  780.57   500.7  781.81   530.1  783.52   608.6  789.36
   618.5  790.86   628.3  793.97   657.7  806.53   667.6  810.28   677.4  812.62
   687.2  813.75     697  815.75   706.8  819.64   716.6  824.48   726.5   829.8
   746.1  841.23   785.4  864.86   824.6  889.94   834.4  895.89   844.3  901.02
#Mann= 3 , 0 , 0
       0     .06       0     349    .045       0     373     .05       0
Bank Sta=349,373
XS Rating Curve= 0 ,0
Exp/Cntr=0.3,0.1

Type RM Length L Ch R = 1 ,11148.4 ,103.2,129.1,154.2
XS GIS Cut Line= 3
     1547086.332      321867.647     1547208.728      322395.425
     1547235.638      322574.244
#Sta/Elev= 30
       0  793.47      29     793    87.1  792.74   106.4  792.36   125.8  791.62
   154.8   789.8   183.8  787.15   193.5  785.81   212.8  782.63   222.5  781.62
   232.2   781.2   321.5  779.44   328.9  779.38   342.5779.8311   367.6  781.44
   406.3  783.64   522.4  789.89   532.1  790.63   541.8  792.29   551.3  795.54
   570.3   804.4   579.8  807.17   598.9  809.56   608.4  812.24   617.9  815.98
     637  824.45     656  833.73     675  843.58   703.6  858.79   722.6  868.46
#Mann= 3 , 0 , 0
       0     .06       0   321.5    .045       0   342.5     .05       0
Bank Sta=321.5,342.5
XS Rating Curve= 0 ,0
Exp/Cntr=0.3,0.1

Type RM Length L Ch R = 1 ,11019.3 ,89.1,89.5,157
XS GIS Cut Line= 6
     1547062.983      321904.556      1547111.71      322140.139
     1547060.755      322154.722     1546994.783      322208.194
      1546982.63      322271.736     1547095.651      322616.267
#Sta/Elev= 30
       0  792.93    67.4  792.46    86.6  791.92   105.8     791   134.7  788.98
   144.3  788.17     154  787.09   182.8  782.32   192.5  781.28   202.1   780.9
   293.6  779.72   312.4  778.95   321.9  778.48   331.3  778.47   340.8  779.04
   350.2  779.78   359.6  780.25   462.8  782.49   482.4  783.18     502  784.23
   531.4   786.2   560.8  788.72     649  797.68   658.8  800.15   668.6     803
   678.4  804.38   688.2  806.26     698  810.42   776.4  854.57   805.8   870.8
#Mann= 3 , 0 , 0
       0     .06       0   312.4    .045       0   340.8     .05       0
Bank Sta=312.4,340.8
XS Rating Curve= 0 ,0
Exp/Cntr=0.3,0.1

Type RM Length L Ch R = 1 ,10929.8 ,251.7,222.3,124.5
XS GIS Cut Line= 6
     1547002.219      321828.601     1547062.406      322068.655
     1547011.451      322083.238     1546945.479      322136.711
     1546933.326      322200.252     1547046.347      322544.783
#Sta/Elev= 30
       0  796.29    38.1  794.25    66.6  793.12   142.8  792.07   171.3  791.41
   218.9  789.02     238   787.4   247.5  786.04   300.5  785.37   319.4  783.16
   338.2  779.41   343.4778.7094   347.7  778.13   357.1  777.76     376  778.33
   394.6  779.26   450.1  779.87   508.9  781.18   548.1  782.32   577.5  783.54
   606.9  785.44   646.1  788.52   734.3  797.24   744.1  798.52   753.9  801.83
   763.7  804.22   773.5   805.2   783.3  808.46   793.1  813.65   812.7  824.74
#Mann= 3 , 0 , 0
       0     .06       0   343.4    .045       0     376     .06       0
Bank Sta=343.4,376
XS Rating Curve= 0 ,0
Exp/Cntr=0.3,0.1