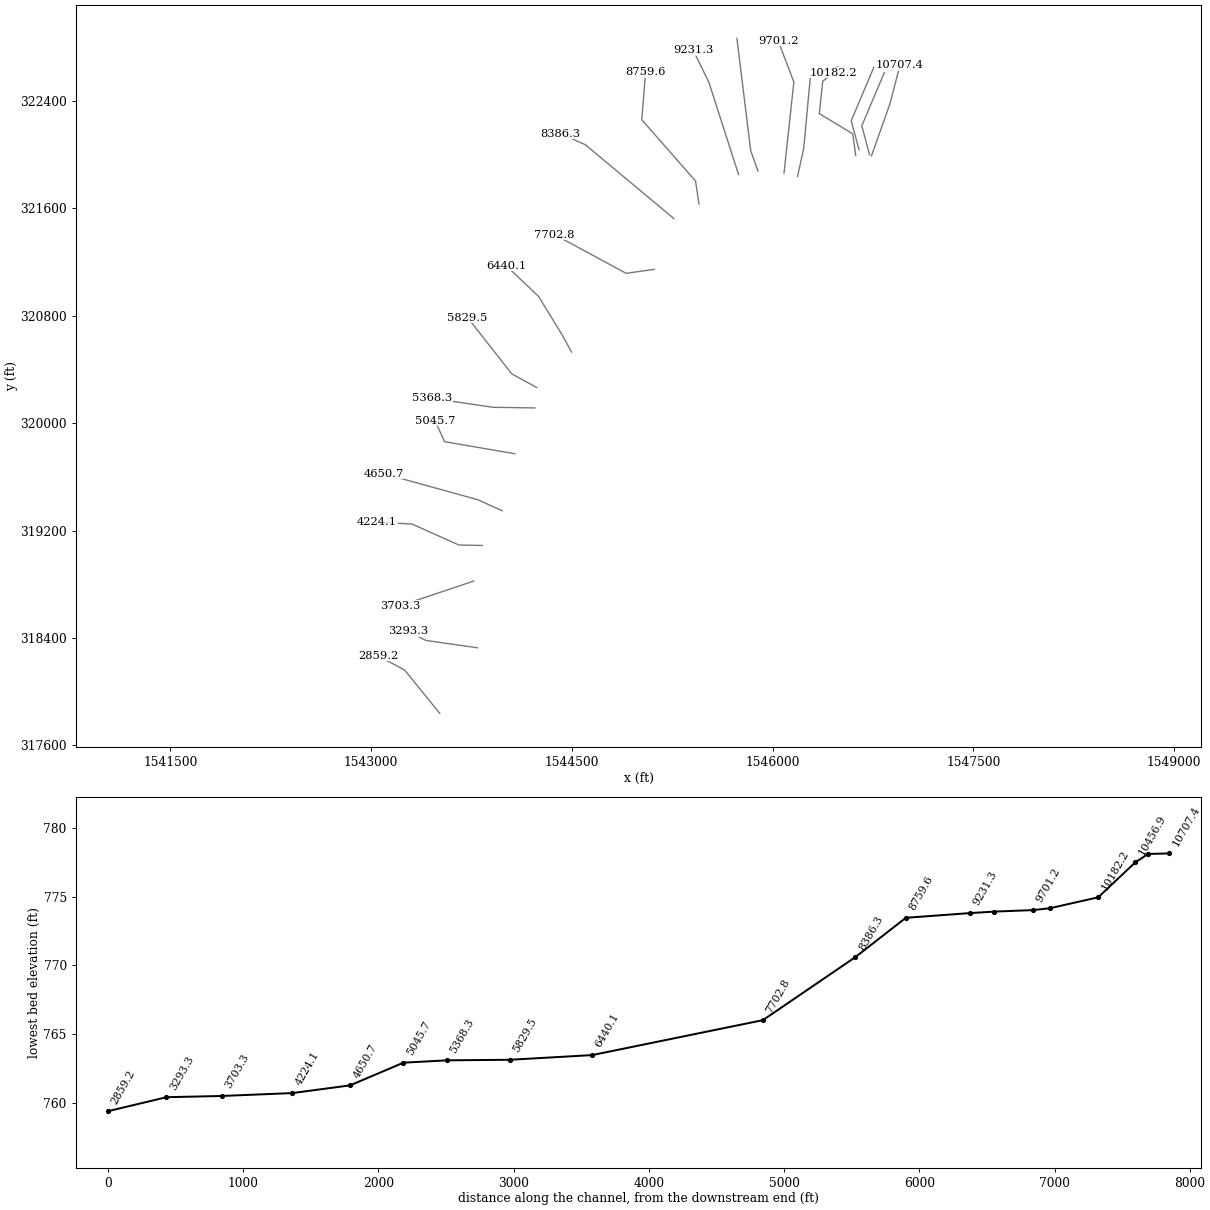
HEC-RAS study MCKIMCRK.prj: MCKIMCRK

--- MCKIMCRK.g01 (geometry) --- (continued)

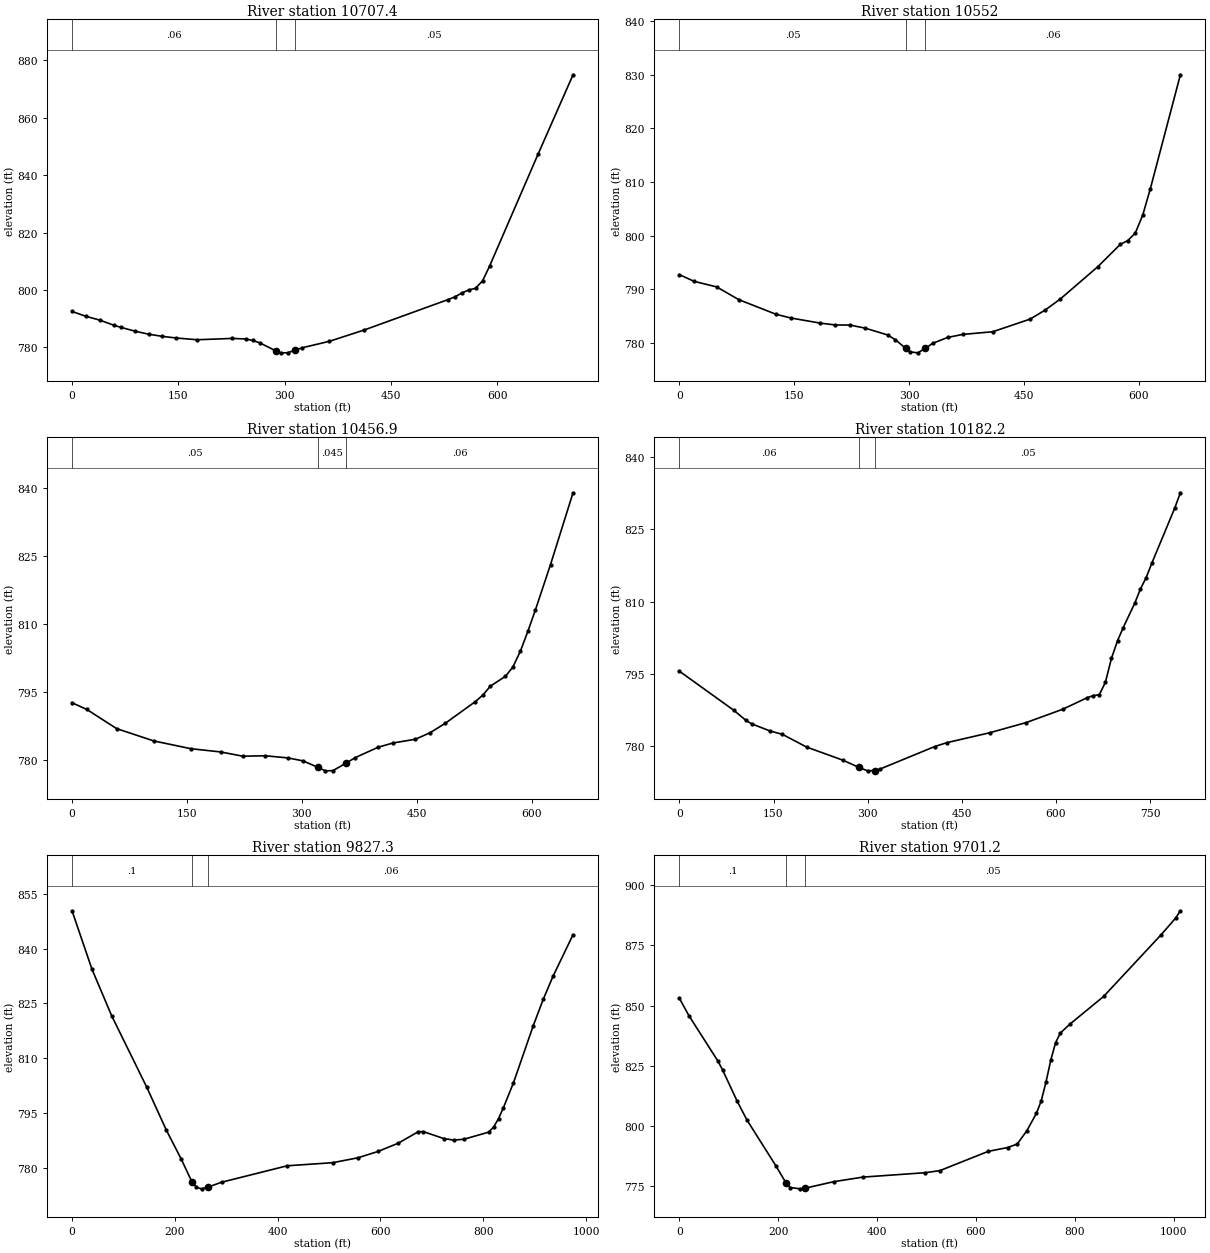
Type RM Length L Ch R = 1 ,10707.4 ,156.8,155.4,154.1
XS GIS Cut Line= 3
     1546739.424      321989.481     1546877.705      322377.675
     1546951.924      322662.832
#Sta/Elev= 30
       0  792.55    19.6  790.86    39.2  789.53    58.9  787.76    68.7  787.04
    88.3  785.72   107.9  784.64   127.6  783.87   147.2   783.3   176.6   782.7
   225.7  783.16   245.3  782.97   255.1  782.44   264.9   781.6   287.9  778.78
   294.4  778.14   304.2  778.17     314     779   323.8  779.85     363  782.16
   412.1  786.09     530  796.65   539.8  797.61   549.6  798.94   559.4  800.04
   569.2  800.62   579.1  803.22   588.9  808.29   657.6  847.47   706.7  874.99
#Mann= 3 , 0 , 0
       0     .06       0   287.9    .045       0     314     .05       0
Bank Sta=287.9,314
XS Rating Curve= 0 ,0
Exp/Cntr=0.3,0.1

Type RM Length L Ch R = 1 ,10552   ,93.5,95,94.8
XS GIS Cut Line= 3
     1546725.144      321997.332     1546666.984      322212.609
     1546835.387      322609.311
#Sta/Elev= 30
       0   792.7    19.4  791.44    48.5  790.42    77.6  788.03     126  785.31
   145.4  784.61   184.2  783.64   203.6  783.31     223  783.28   242.6  782.71
     272  781.43   281.8  780.56  295.24778.9714   301.4  778.28   311.2   778.1
   320.9  778.92   330.7  779.88   350.3  780.98   369.9  781.54   409.1  782.04
   458.1  784.41   477.7  786.11   497.2  788.14   546.2  794.18   575.6  798.35
   585.4  799.07   595.2  800.47     605  803.87   614.8  808.74     654  830.02
#Mann= 3 , 0 , 0
       0     .05       0  295.24    .045       0   320.9     .06       0
Bank Sta=295.24,320.9
XS Rating Curve= 0 ,0
Exp/Cntr=0.3,0.1

Type RM Length L Ch R = 1 ,10456.9 ,242.7,274.8,307.5
XS GIS Cut Line= 3
     1546646.151      322035.092     1546587.991       322250.37
     1546756.394      322647.071
#Sta/Elev= 30
       0  792.56    19.4  791.07    58.2  786.84   106.6  784.12   155.1   782.4
   193.9  781.68     223  780.74   252.4  780.83   281.8  780.36   301.4  779.71
   320.9  778.28   330.7   777.5   340.5  777.54  357.75779.1986   369.9  780.44
   399.3   782.7   418.9  783.66   448.3  784.49   467.9  785.97   487.4  788.04
   526.6  792.83   536.4  794.28   546.2  796.25   565.8  798.41   575.6   800.5
   585.4  804.02   595.2  808.43     605  813.15   624.6  823.13     654  839.01
#Mann= 3 , 0 , 0
       0     .05       0   320.9    .045       0  357.75     .06       0
Bank Sta=320.9,357.75
XS Rating Curve= 0 ,0
Exp/Cntr=0.3,0.1

Type RM Length L Ch R = 1 ,10182.2 ,380.7,354.8,328.5
XS GIS Cut Line= 5
     1546621.922      321990.911     1546599.353      322153.237
     1546349.353      322303.411     1546375.395      322544.731
      1546453.52      322607.231
#Sta/Elev= 30
       0  795.58    86.8  787.48     106   785.4   115.7  784.65   144.6   783.2
   163.9  782.52   202.8  779.87   261.1  777.13   286.1775.6572     300  774.95
   311.1  775.01   319.4   775.3   406.9  779.98   426.4  780.79   494.4  782.83
   552.6  784.94   610.9   787.7   649.7  790.08   659.4  790.52   669.1  790.72
   678.8  793.25   688.5  798.24   698.2  801.89   707.3  804.62   725.5  809.62
   734.6  812.57   743.7  814.92   752.8  817.93   789.2   829.3   798.3  832.51
#Mann= 3 , 0 , 0
       0     .06       0   286.1    .045       0   311.1     .05       0
Bank Sta=286.1,311.1
XS Rating Curve= 0 ,0
Exp/Cntr=0.3,0.1

Type RM Length L Ch R = 1 ,9827.3  ,126.5,126.2,125.8
XS GIS Cut Line= 4
     1546186.972      321835.832     1546232.882      322043.464
     1546283.803      322590.606     1546487.796      322650.285
#Sta/Elev= 30
       0  850.34    38.7  834.36    77.3  821.52     145  802.12   183.6  790.21
   212.6  782.27     233 776.139   242.1  774.57   251.9  774.16   264.8 774.653
   291.2  775.98   418.7  780.48     507  781.32   556.1  782.66   595.3   784.4
   634.6  786.66   673.8  789.82   683.6  789.83   722.9  787.95   742.5  787.52
   762.2  787.74   810.5  789.69   820.1  791.06   829.8  793.41   839.4  796.44
   858.8   803.2   897.4   818.9   916.7  826.07     936  832.47   974.7  843.78
#Mann= 3 , 0 , 0
       0      .1       0     233    .045       0   264.8     .06       0
Bank Sta=233,264.8
XS Rating Curve= 0 ,0
Exp/Cntr=0.3,0.1

Type RM Length L Ch R = 1 ,9701.2  ,282.9,288.4,293.9
XS GIS Cut Line= 3
     1546085.778      321860.141     1546159.276      322539.418
     1546041.003      322847.578
#Sta/Elev= 30
       0  853.05    19.5  845.77    78.1  826.96    87.8  823.17   117.1  810.28
   136.6   802.6   195.2  783.57   216.1 776.336   224.5  774.57     244  774.02
   253.5 774.253   312.3  776.99   370.9  778.88   497.8  780.72   527.1  781.59
   624.7  789.56   663.7  791.14   683.2  792.57   702.7  798.09   722.1   805.3
   731.8  810.44   741.5  818.28   751.2  827.36   760.9  834.63   770.6  838.63
     790  842.34     858  853.78   974.5  879.41  1003.6  886.26  1013.3  889.32
#Mann= 3 , 0 , 0
       0      .1       0   216.1    .045       0   253.5     .05       0
Bank Sta=216.1,253.5
XS Rating Curve= 0 ,0
Exp/Cntr=0.3,0.1

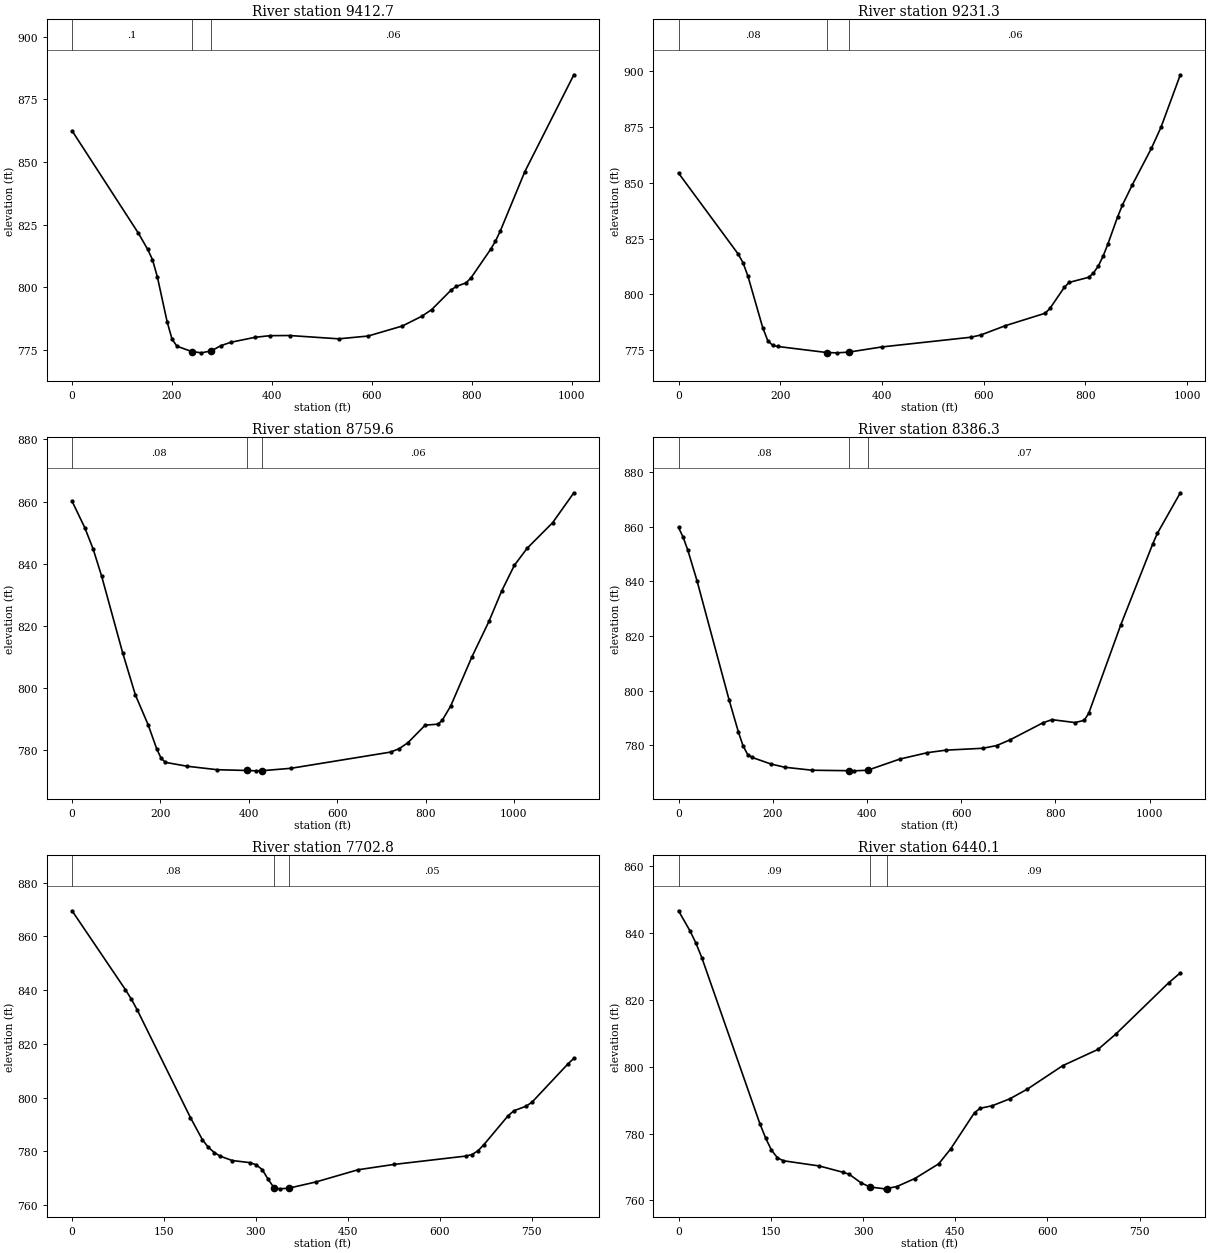
Type RM Length L Ch R = 1 ,9412.7  ,177.4,181.5,185.9
XS GIS Cut Line= 3
     1545891.241      321875.602     1545836.987      322027.077
     1545733.688      322863.883
#Sta/Elev= 30
       0   862.5   132.5  821.71   151.4  815.16   160.9   811.1   170.7  804.18
   190.3  786.23   200.1  779.35   209.9  776.56   239.3  774.44   258.9  773.91
   278.6  774.71   298.2   776.8   317.8  778.13   366.8  780.13   396.2  780.76
   435.4  780.82   533.5   779.5   592.3  780.61   660.9  784.62   700.1  788.53
   719.7  791.18     759  799.06   768.8   800.4   788.4  801.83   798.2  803.79
   837.4  815.16   847.2  818.45     857  822.57     906   846.2  1004.1  884.84
#Mann= 3 , 0 , 0
       0      .1       0   239.3    .045       0   278.6     .06       0
Bank Sta=239.3,278.6
XS Rating Curve= 0 ,0
Exp/Cntr=0.3,0.1

Type RM Length L Ch R = 1 ,9231.3  ,462,471.7,480.3
XS GIS Cut Line= 3
     1545745.934      321850.592      1545524.58      322536.356
     1545407.392      322775.071
#Sta/Elev= 30
       0  854.36   116.8  818.22   126.6  814.26   136.3  808.28   165.5  785.11
   175.3  779.33     185  777.16   194.8  776.66   292.1  773.92   311.6   773.8
  334.85774.1224   399.2  776.43   574.5  780.79     594  781.77   642.7  785.98
   720.6  791.53   730.1  793.69   758.6  803.22   768.1  805.37   806.1  807.64
   815.6  809.56   825.1  812.65   834.6  817.09   844.1  822.57   863.1  834.68
   872.6  839.99   891.6  848.88   929.6  865.42   948.5  874.91   986.5  898.42
#Mann= 3 , 0 , 0
       0     .08       0   292.1    .045       0  334.85     .06       0
Bank Sta=292.1,334.85
XS Rating Curve= 0 ,0
Exp/Cntr=0.3,0.1

Type RM Length L Ch R = 1 ,8759.6  ,369.7,373.3,376.7
XS GIS Cut Line= 4
     1545450.448      321631.379      1545424.63       321801.41
     1545022.991       322257.72      1545051.49      322612.311
#Sta/Elev= 30
       0  860.09    28.7  851.62    47.8  844.69    66.9  836.03   114.6  811.34
   143.3  797.84     172  788.32   191.6  780.51   201.4  777.54   211.2  776.19
   260.2  774.94   328.8  773.82   394.8773.5782   417.1  773.46   429.7   773.5
   495.5  774.28     721  779.49   740.6   780.6   760.3  782.53   799.1  788.14
   827.9  788.46   837.6  789.67   856.8  794.28   904.9  810.08   943.3  821.45
   972.2  831.24    1001  839.51  1029.8  844.97  1087.5  853.19  1135.6  862.81
#Mann= 3 , 0 , 0
       0     .08       0   394.8    .045       0   429.7     .06       0
Bank Sta=394.8,429.7
XS Rating Curve= 0 ,0
Exp/Cntr=0.3,0.1

Type RM Length L Ch R = 1 ,8386.3  ,678,683.5,688.6
XS GIS Cut Line= 3
     1545263.729      321521.223     1544601.623      322071.739
     1544415.205      322154.903
#Sta/Elev= 30
       0   859.8     9.8  856.21    19.6  851.53    39.1  840.34   107.6  796.43
   127.2  784.76     137  779.75   146.8  776.56   156.6  775.49   195.7  773.13
     225  771.93   283.8  770.82     362  770.65   371.8   770.6   401.2  770.81
   469.7  774.91   528.4  777.26   567.5  778.18   645.8  778.87   675.2  779.86
   704.5  782.02     773  788.16   792.6  789.36   841.5   788.3   861.1  789.09
   870.8  791.71   938.8   824.1  1006.9  853.88  1016.6  857.69  1065.2  872.51
#Mann= 3 , 0 , 0
       0     .08       0     362    .045       0   401.2     .07       0
Bank Sta=362,401.2
XS Rating Curve= 0 ,0
Exp/Cntr=0.3,0.1

Type RM Length L Ch R = 1 ,7702.8  ,1281.6,1262.7,1231.9
XS GIS Cut Line= 3
      1545116.34       321143.98     1544905.837      321114.684
     1544371.983      321402.227
#Sta/Elev= 30
       0  869.55      87   840.2    96.6  836.71   106.3  832.65   193.2  792.53
   212.5  784.39   222.3  781.49   232.1  779.55   241.9  778.17   261.4  776.56
   290.8  775.76   300.6  774.95   310.3  773.19   320.1  769.53   329.9  766.34
   339.7  766.02  354.01766.2817   398.4  768.61   466.8  773.13   525.5  775.11
   642.9  778.23   652.6  778.79   662.4  780.17   672.2   782.5   711.3  793.16
   721.1   795.1   740.7  796.77   750.4  798.23   809.1   812.5   818.9  814.62
#Mann= 3 , 0 , 0
       0     .08       0   329.9    .045       0  354.01     .05       0
Bank Sta=329.9,354.01
XS Rating Curve= 0 ,0
Exp/Cntr=0.3,0.1

Type RM Length L Ch R = 1 ,6440.1  ,592,610.6,623.2
XS GIS Cut Line= 4
     1544497.877      320528.498     1544425.178      320661.007
     1544252.131        320942.3     1544008.988      321172.248
#Sta/Elev= 30
       0   846.6    18.9   840.5    28.3  836.93    37.8  832.61   132.2     783
   141.7  778.65   151.1  775.07   160.9  772.74   170.6  771.87   228.8  770.32
   267.7  768.42   277.4  767.85   296.8  765.28   311.4764.0237   335.7  763.48
   338.4  763.56   355.1  764.17   384.3  766.56   423.1  770.95   442.6  775.42
   481.4  786.27     491  787.58   510.1  788.31   538.8  790.39   567.5  793.31
   624.8   800.3   682.2  805.16   710.9  809.69   796.9  825.03   816.1  828.04
#Mann= 3 , 0 , 0
       0     .09       0   311.4    .045       0   338.4     .09       0
Bank Sta=311.4,338.4
XS Rating Curve= 0 ,0
Exp/Cntr=0.3,0.1

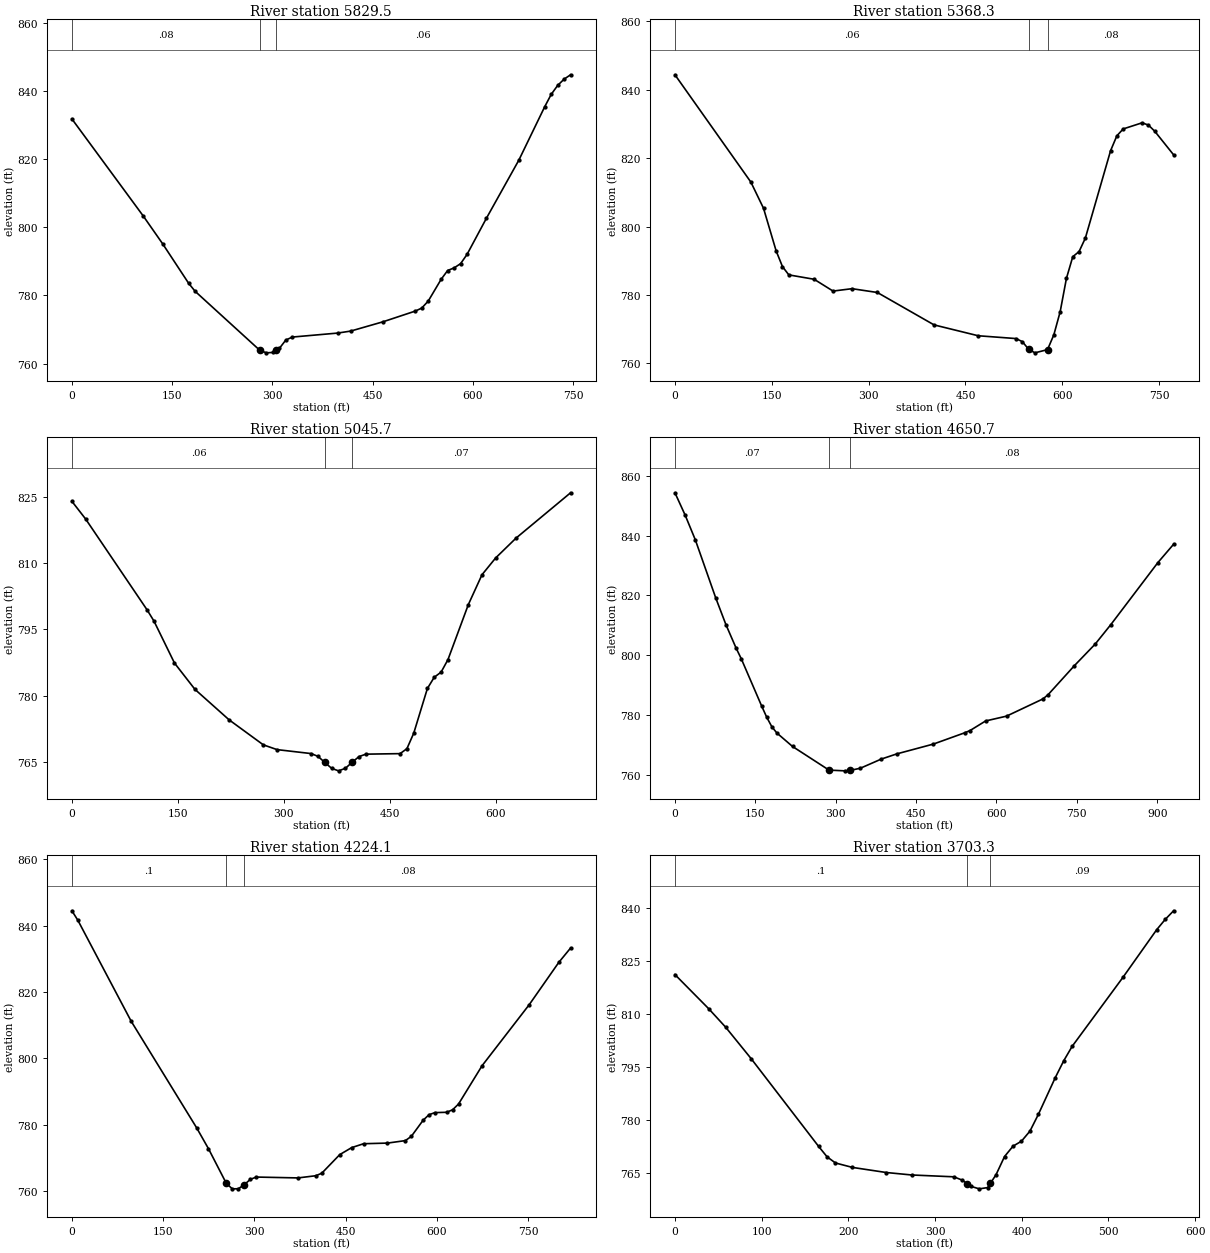
Type RM Length L Ch R = 1 ,5829.5  ,443.2,461.2,478.3
XS GIS Cut Line= 3
     1544238.722      320264.061     1544051.222      320366.492
     1543721.361      320784.895
#Sta/Elev= 30
       0  831.91   106.8  803.37     136  795.15   174.8  783.57   184.5  781.22
   281.5  763.84   291.2  763.14   300.8  763.26   305.5  763.83   310.5  764.44
   320.2  766.91   329.9  767.78   397.7  768.95   417.1  769.53   465.5  772.26
     514  775.42   523.6   776.3   533.3  778.35   552.7  784.77   562.4  787.35
   572.1  788.12   581.8  789.37   591.4  792.07   620.5  802.74     669  819.81
   707.7  835.51   717.4  839.13   727.1  841.78   736.8  843.63   746.4   844.9
#Mann= 3 , 0 , 0
       0     .08       0   281.5    .045       0   305.5     .06       0
Bank Sta=281.5,305.5
XS Rating Curve= 0 ,0
Exp/Cntr=0.3,0.1

Type RM Length L Ch R = 1 ,5368.3  ,323.4,322.6,321.4
XS GIS Cut Line= 3
     1544223.213      320112.441     1543909.729       320117.36
     1543455.736        320184.2
#Sta/Elev= 30
       0  844.32   117.6  812.98   137.2  805.33   156.8  792.85   166.6  788.27
   176.4  785.87   215.6  784.59   244.9  781.14   274.3  781.84   313.5  780.73
   401.4  771.26   469.7  768.09   528.3  767.27   538.1  766.37   547.8  764.16
   557.6   763.1   577.1  764.04   586.9  768.36   596.7  775.11   606.4  784.85
   616.2  791.17     626  792.69   635.7  796.61   674.8  822.15   684.5  826.49
   694.3   828.5   723.6  830.29   733.4  829.63   743.1  827.85   772.4  820.94
#Mann= 3 , 0 , 0
       0     .06       0   547.8    .045       0   577.1     .08       0
Bank Sta=547.8,577.1
XS Rating Curve= 0 ,0
Exp/Cntr=0.3,0.1

Type RM Length L Ch R = 1 ,5045.7  ,396.6,395,393.1
XS GIS Cut Line= 3
     1544074.341      319771.491     1543549.601      319861.334
     1543476.685      320018.886
#Sta/Elev= 30
       0     824    19.4     820   106.5  799.39   116.2  796.86   145.2  787.36
   174.2  781.39   222.6  774.48     271  768.82   290.4  767.74   338.8  766.84
   348.5   766.2   358.1  764.82   367.8  763.49   377.5  762.93   387.2   763.5
   396.9   764.9   406.5  766.16   416.2  766.71   464.6  766.83   474.3  767.95
     484  771.48   503.3   781.6     513  784.14   522.7   785.3   532.4  788.13
   561.3  800.62   580.6  807.37   599.9  811.17   628.8  815.67     706  825.94
#Mann= 3 , 0 , 0
       0     .06       0   358.1    .045       0   396.9     .07       0
Bank Sta=358.1,396.9
XS Rating Curve= 0 ,0
Exp/Cntr=0.3,0.1

Type RM Length L Ch R = 1 ,4650.7  ,430.2,426.6,423
XS GIS Cut Line= 3
     1543978.963      319347.445     1543796.672      319429.477
     1543092.245      319623.487
#Sta/Elev= 30
       0  854.32      19  846.87    38.1  838.55    76.2  819.11    95.2  810.18
   114.2  802.33   123.8  798.78   161.8  782.98   171.3  779.21   180.9  776.01
   190.4  773.91   219.4  769.44   287.6  761.52   316.8  761.28   326.6  761.42
     346  762.15     385  765.21   414.2  766.96   482.4  770.24   540.9  774.02
   550.6  774.75   579.8  777.97   618.8  779.58     687  785.36   696.7  786.82
   745.4  796.46   784.4  803.72   813.6  810.24   901.3  830.97   930.6   837.1
#Mann= 3 , 0 , 0
       0     .07       0   287.6    .045       0   326.6     .08       0
Bank Sta=287.6,326.6
XS Rating Curve= 0 ,0
Exp/Cntr=0.3,0.1

Type RM Length L Ch R = 1 ,4224.1  ,503.7,520.8,537.6
XS GIS Cut Line= 4
     1543831.643      319088.825     1543656.216      319091.912
     1543306.763      319248.149     1543045.261      319262.254
#Sta/Elev= 30
       0  844.48     9.8  841.61    97.5  811.19   204.9  779.17   224.5  772.84
     254  762.35   263.8  760.72   273.6  760.74   283.4  761.96   293.2  763.54
     303  764.27   371.8  764.01   401.2  764.67     411  765.44   440.5  771.03
   460.1  773.14   479.7  774.31     519   774.5   548.4  775.25   558.2  776.53
   577.6  781.38   587.3  783.05     597  783.68   616.4  783.78   626.1  784.54
   635.8  786.26   674.6  797.82   752.2  816.22   800.7  828.93   820.1  833.26
#Mann= 3 , 0 , 0
       0      .1       0     254    .045       0   283.4     .08       0
Bank Sta=254,283.4
XS Rating Curve= 0 ,0
Exp/Cntr=0.3,0.1

Type RM Length L Ch R = 1 ,3703.3  ,420.2,409.9,399.3
XS GIS Cut Line= 2
     1543766.688      318823.597     1543221.115      318641.305
#Sta/Elev= 30
       0   821.1      39  811.43    58.5  806.22    87.8  797.36   165.7  772.52
   175.5  769.56   185.2  767.82   204.7  766.57   243.7  765.13     273  764.43
   321.7  763.91   331.5  762.96  337.42761.9042   341.2  761.23     351  760.51
   360.7  760.86  363.98762.0984   370.5  764.56   380.2  769.65     390  772.58
   399.7  773.98   409.5  776.83   419.2  781.56   438.7  791.95   448.5  796.74
   458.2  800.81   516.7  820.29   555.7  833.79   565.5  836.69   575.2  839.14
#Mann= 3 , 0 , 0
       0      .1       0  337.42    .045       0  363.98     .09       0
Bank Sta=337.42,363.98
XS Rating Curve= 0 ,0
Exp/Cntr=0.3,0.1

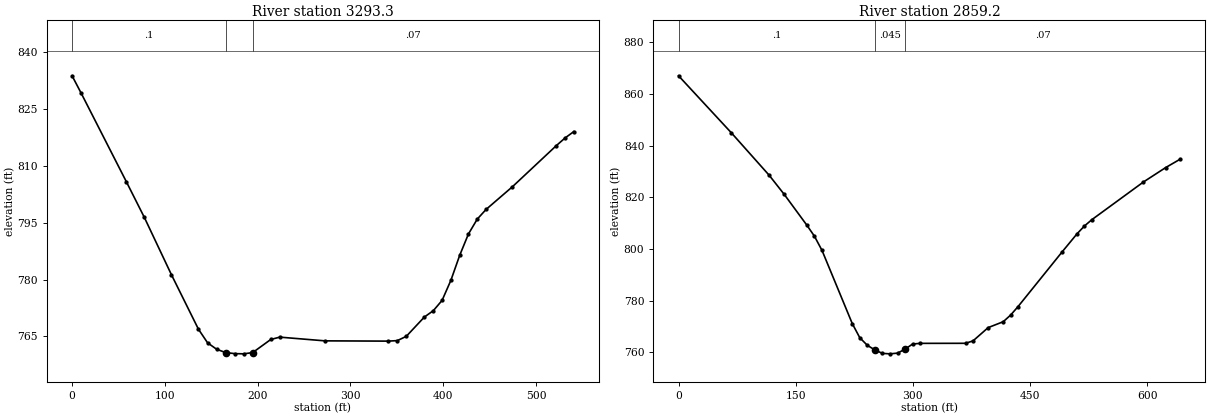
Type RM Length L Ch R = 1 ,3293.3  ,451,434.1,417.3
XS GIS Cut Line= 3
       1543794.9      318327.069     1543409.483      318381.757
     1543275.368      318452.069
#Sta/Elev= 30
       0  833.67     9.7  829.14    58.4  805.81    77.9  796.35     107   781.3
   136.2   766.9     146  763.33   155.7  761.64   165.4  760.76   175.2  760.48
   184.9  760.42   194.6  760.75   214.1   764.2   223.8  764.82   272.5  763.84
   340.6  763.77   350.4   763.9   360.1  765.02   379.6  770.11   389.3   771.8
   398.7   774.5   408.2  779.79   417.7  786.38   427.1  791.99   436.6  795.91
   446.1  798.46   474.5  804.44   521.8  815.27   531.2  817.28   540.7  818.98
#Mann= 3 , 0 , 0
       0      .1       0   165.4    .045       0   194.6     .07       0
Bank Sta=165.4,194.6
XS Rating Curve= 0 ,0
Exp/Cntr=0.3,0.1

Type RM Length L Ch R = 1 ,2859.2  ,213.1,210.8,208.3
XS GIS Cut Line= 3
      1543513.65      317838.788     1543250.914      318160.917
     1543051.261      318268.339
#Sta/Elev= 30
       0  867.07    67.7  844.96     116  828.56   135.3  821.15   164.3  809.21
     174  804.94   183.7  799.44   222.4  771.13     232  765.66   241.7   762.7
   251.4   760.9     261  759.58   270.7   759.4   280.4  759.68     290  761.22
   299.7   763.2   309.4  763.46   367.4  763.48     377  764.41   396.4  769.56
   415.7  771.84   425.1   774.4   434.6  777.68   491.3  798.96   510.2  805.89
   519.6  808.89     529  811.32   595.2  825.95   623.5   831.5   642.4  834.81
#Mann= 3 , 0 , 0
       0      .1       0   251.4    .045       0     290     .07       0
Bank Sta=251.4,290
XS Rating Curve= 0 ,0
Exp/Cntr=0.3,0.1