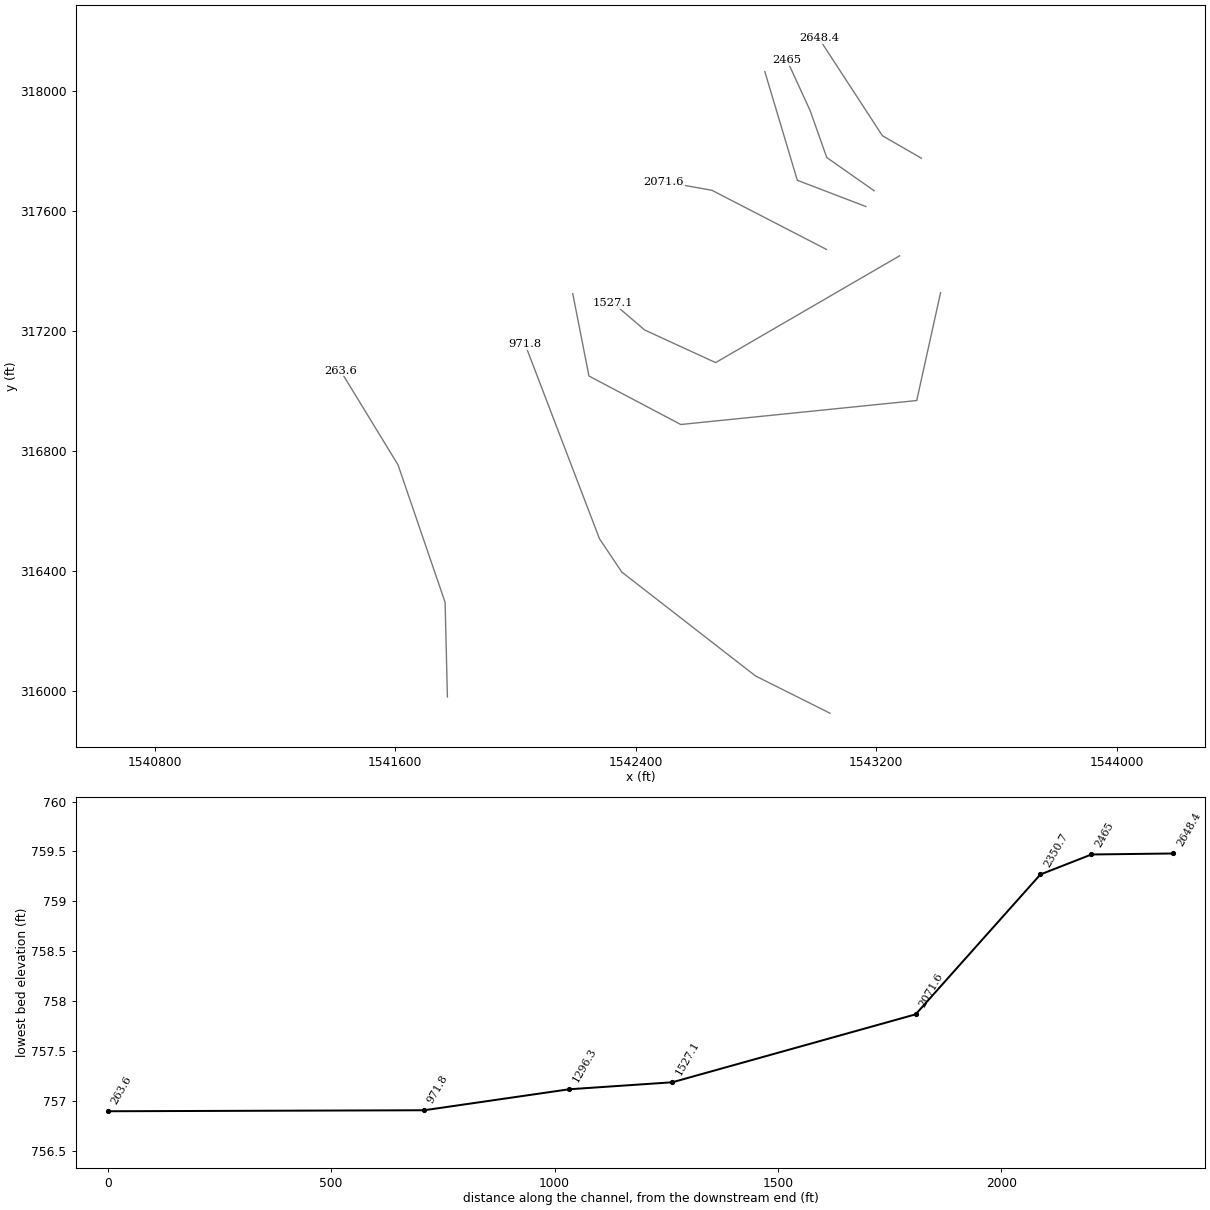
HEC-RAS study MCKIMCRK.prj: MCKIMCRK

--- MCKIMCRK.g01 (geometry) --- (continued)

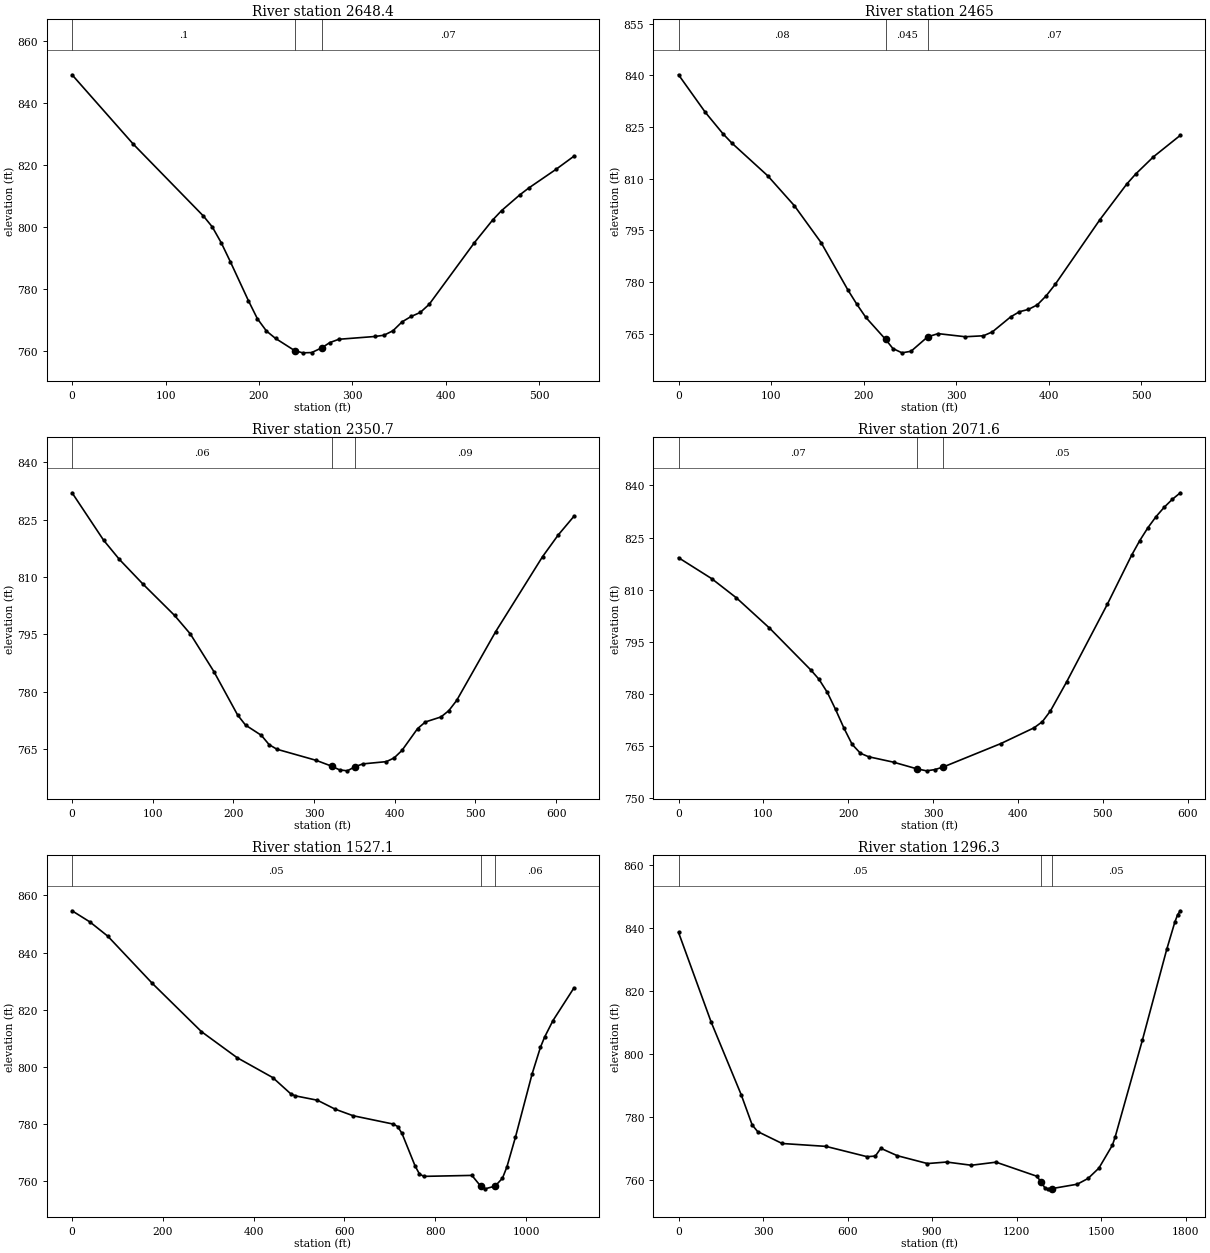
Type RM Length L Ch R = 1 ,2648.4  ,188.6,183.4,177.8
XS GIS Cut Line= 3
     1543350.308      317774.809     1543220.447      317849.809
     1543009.336      318174.114
#Sta/Elev= 30
       0  849.07    65.6  826.69   140.6  803.54     150  800.07   159.6  794.95
   169.3  788.88   188.7  776.28   198.3  770.46     208   766.5   217.7  764.13
   238.2760.1905   246.7  759.48   256.4  759.57   267.2761.0963   275.7  762.77
   285.4  763.85   324.1  764.75   333.8  765.16   343.4  766.61   353.1  769.46
   362.8   771.2   372.5  772.48   382.1  775.11   430.5  794.98   449.9  802.24
   459.5  805.29   478.9  810.34   488.6  812.58   517.6  818.56   536.9  822.82
#Mann= 3 , 0 , 0
       0      .1       0   238.2    .045       0   267.2     .07       0
Bank Sta=238.2,267.2
XS Rating Curve= 0 ,0
Exp/Cntr=0.3,0.1

Type RM Length L Ch R = 1 ,2465    ,115.4,114.3,113.3
XS GIS Cut Line= 4
     1543193.135      317666.604     1543035.462       317777.15
     1542979.991       317933.71     1542903.552      318100.459
#Sta/Elev= 30
       0  840.14    28.9  829.26    48.1     823    57.8  820.28    96.3  810.85
   125.2  802.14     154  791.46   182.9  777.74   192.6  773.58   202.3  769.77
   223.7 763.367   231.6  760.72   241.4  759.47   251.2  759.93   269.2 764.127
   280.5  765.04   309.8  764.14   329.4  764.42   339.1  765.56   358.7  769.88
   368.3   771.4     378  772.07   387.6  773.39   397.3  776.05   406.9  779.33
   455.2   798.1   484.2  808.43   493.8  811.33   513.1  816.35   542.1  822.58
#Mann= 3 , 0 , 0
       0     .08       0   223.7    .045       0   269.2     .07       0
Bank Sta=223.7,269.2
XS Rating Curve= 0 ,0
Exp/Cntr=0.3,0.1

Type RM Length L Ch R = 1 ,2350.7  ,262.1,279.1,296.8
XS GIS Cut Line= 3
     1543165.549      317614.001     1542937.424      317701.501
     1542829.421      318063.341
#Sta/Elev= 30
       0  832.07    39.1  819.65    58.6  814.64      88  808.14     127  799.97
   146.6  795.11   175.9  785.22   205.2  773.89     215  771.25   234.6  768.57
   244.3  766.12     254  764.92   302.4  762.03   321.8  760.49   331.5  759.53
   341.2  759.27   350.8  760.36   360.5  761.09   389.6  761.68   399.2  762.65
   408.9  764.61   428.3  770.33     438  772.07   457.3  773.38     467  775.03
   476.7  777.69   525.1  795.72   583.2  815.35   602.6  821.02     622  825.89
#Mann= 3 , 0 , 0
       0     .06       0   321.8    .045       0   350.8     .09       0
Bank Sta=321.8,350.8
XS Rating Curve= 0 ,0
Exp/Cntr=0.3,0.1

Type RM Length L Ch R = 1 ,2071.6  ,541.7,544.5,546
XS GIS Cut Line= 3
     1543034.418       317471.21     1542653.553      317668.115
     1542493.397      317696.761
#Sta/Elev= 30
       0  819.19      39  813.18    68.2  807.64   107.2  798.95   155.9  786.89
   165.6  784.19   175.4  780.42   185.1  775.52   194.9  770.19   204.6  765.49
   214.4  762.92   224.1  761.92   253.4  760.36   280.6758.4669   292.3  757.87
   302.1  758.23   311.8  758.96     380  765.73     419  770.25   428.8  772.01
   438.3   775.1   457.5  783.51   505.3  805.76     534   819.9   543.6  824.12
   553.2  827.82   562.7  830.98   572.3  833.68   581.9  835.98   591.4  837.87
#Mann= 3 , 0 , 0
       0     .07       0   280.6    .045       0   311.8     .05       0
Bank Sta=280.6,311.8
XS Rating Curve= 0 ,0
Exp/Cntr=0.3,0.1

Type RM Length L Ch R = 1 ,1527.1  ,231.9,230.8,229.1
XS GIS Cut Line= 4
     1543277.471      317449.862     1542665.706      317094.331
     1542429.687      317202.937     1542324.913      317292.738
#Sta/Elev= 30
       0  854.63    39.3  850.72    78.6  845.74   176.9  829.17     285  812.28
   363.6  803.15   442.2  796.17   481.5  790.52   491.4  789.79   540.5  788.24
   579.8  785.09   619.1  782.81   707.6  779.88   717.2  779.03   726.8   776.6
   755.7  765.19   765.3  762.38   774.9  761.56   880.8   761.9     900  758.15
   909.6  757.19  932.01758.1487   948.1  760.92   957.8  764.82   976.6  775.23
  1013.4  797.45  1031.8   806.8    1041  810.38  1059.4  816.16  1105.4  827.55
#Mann= 3 , 0 , 0
       0     .05       0     900    .045       0  932.01     .06       0
Bank Sta=900,932.01
XS Rating Curve= 0 ,0
Exp/Cntr=0.3,0.1

Type RM Length L Ch R = 1 ,1296.3  ,340.5,324.4,308
XS GIS Cut Line= 5
     1543414.001       317327.13     1543334.628       316968.08
     1542549.906      316888.219      1542244.35      317049.677
     1542190.531      317323.983
#Sta/Elev= 30
       0  838.64   116.1  810.08   222.6  787.02   261.3  777.47   280.6  775.35
   367.7  771.54   523.5  770.62   669.6  767.34   698.8  767.54   718.3     770
   776.7  767.66   883.8  765.16     952  765.64  1039.6  764.62  1127.3   765.6
  1271.7  761.14  1286.9 759.374  1300.5  757.45  1310.1  757.12  1324.9 757.185
  1415.7  758.59  1454.1  760.43  1492.5  763.71  1540.6  771.03  1550.3  773.63
  1646.7  804.33  1733.4  833.28  1762.3  841.98    1772  844.27  1781.6  845.53
#Mann= 3 , 0 , 0
       0     .05       0  1286.9    .045       0  1324.9     .05       0
Bank Sta=1286.9,1324.9
XS Rating Curve= 0 ,0
Exp/Cntr=0.3,0.1

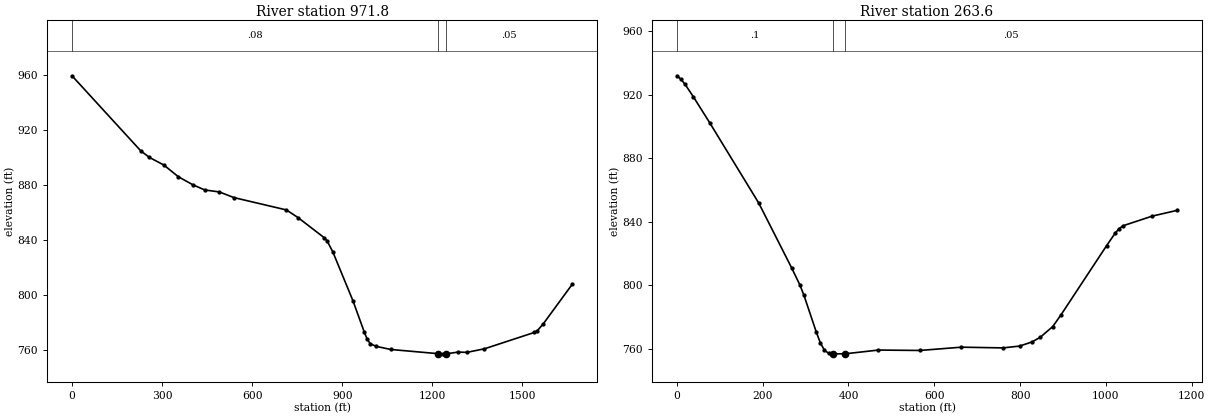
Type RM Length L Ch R = 1 ,971.8   ,704.6,708.3,709.6
XS GIS Cut Line= 5
     1543046.234      315926.878     1542798.587      316050.836
     1542353.728       316396.77     1542279.484      316507.662
     1542032.171      317154.742
#Sta/Elev= 30
       0  959.19   229.2  904.54   257.8  899.81   306.1  894.25   354.7  885.66
   403.2  879.84   442.1  876.12   490.7   874.7   539.3  870.58   714.2  861.59
     753  856.02   840.5  841.33     850  838.97   869.1  830.91   935.8  795.54
   973.9  772.56   983.7  767.36   993.4  764.32    1013  762.36  1061.7  760.09
  1218.9757.0437  1237.4  756.91  1246.9756.9393  1286.1  758.18  1315.4  757.99
    1374  760.58  1539.8  772.46  1549.6  773.67  1569.1  778.52  1666.6  807.61
#Mann= 3 , 0 , 0
       0     .08       0  1218.9    .045       0  1246.9     .05       0
Bank Sta=1218.9,1246.9
XS Rating Curve= 0 ,0
Exp/Cntr=0.3,0.1

Type RM Length L Ch R = 1 ,263.6   ,273.2,263.6,253.5
XS GIS Cut Line= 4
     1541773.564      315981.112     1541765.926      316296.043
     1541609.387      316753.664      1541417.98      317067.466
#Sta/Elev= 30
       0  931.88     9.6  929.67    19.1  926.52    38.2  918.77    76.4  902.38
   190.9  851.76   267.3  811.11   286.4  800.46   295.9  793.98   324.7  770.81
   334.4  763.83     344  759.18   353.7  757.25   363.4   756.9   392.4  756.93
   469.8  759.28   566.5  759.03   663.2  761.09     760  760.64   798.7  761.78
   827.7  764.38     847  767.33   876.1  774.06   895.4  781.46  1001.8  825.05
  1021.2  832.67  1030.8  835.73  1040.5  837.55  1108.2  843.59  1166.2   847.2
#Mann= 3 , 0 , 0
       0      .1       0   363.4    .045       0   392.4     .05       0
Bank Sta=363.4,392.4
XS Rating Curve= 0 ,0
Exp/Cntr=0.3,0.1

Chan Stop Cuts=-1
Use User Specified Reach Order=0
Composite Channel Slope=5

--- MCKIMCRK.g02 (geometry) ---

Geom Title=Merged Geometry
Program Version=4.10

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
River Reach=MCKIMCRK        ,Main
Reach XY= 30
     1555559.966      323826.461     1554596.168      322748.338
     1554046.926      321684.656     1553187.061      321535.821
     1553133.395      321182.391     1552213.517      320291.777
     1550970.027      320793.687      1550682.97      321152.396
     1550388.239      320739.902     1550312.073      321001.646
     1549859.599      320956.074     1549654.521      321365.145
     1549299.226      321025.156     1548911.654      321966.505
      1548125.49      321806.436     1548039.119      321994.283
     1546939.778      322117.893     1546596.897      322387.512
       1546399.4      322050.925     1545400.195      322155.827
     1544931.509      321720.256     1544552.771       320751.95
      1544358.76      320982.419     1543667.435      320174.658
      1543753.65      319621.567     1543355.733      318884.892
     1543595.751       318243.79     1542787.046      317747.557
     1542005.362      316476.333     1541488.944      316417.618

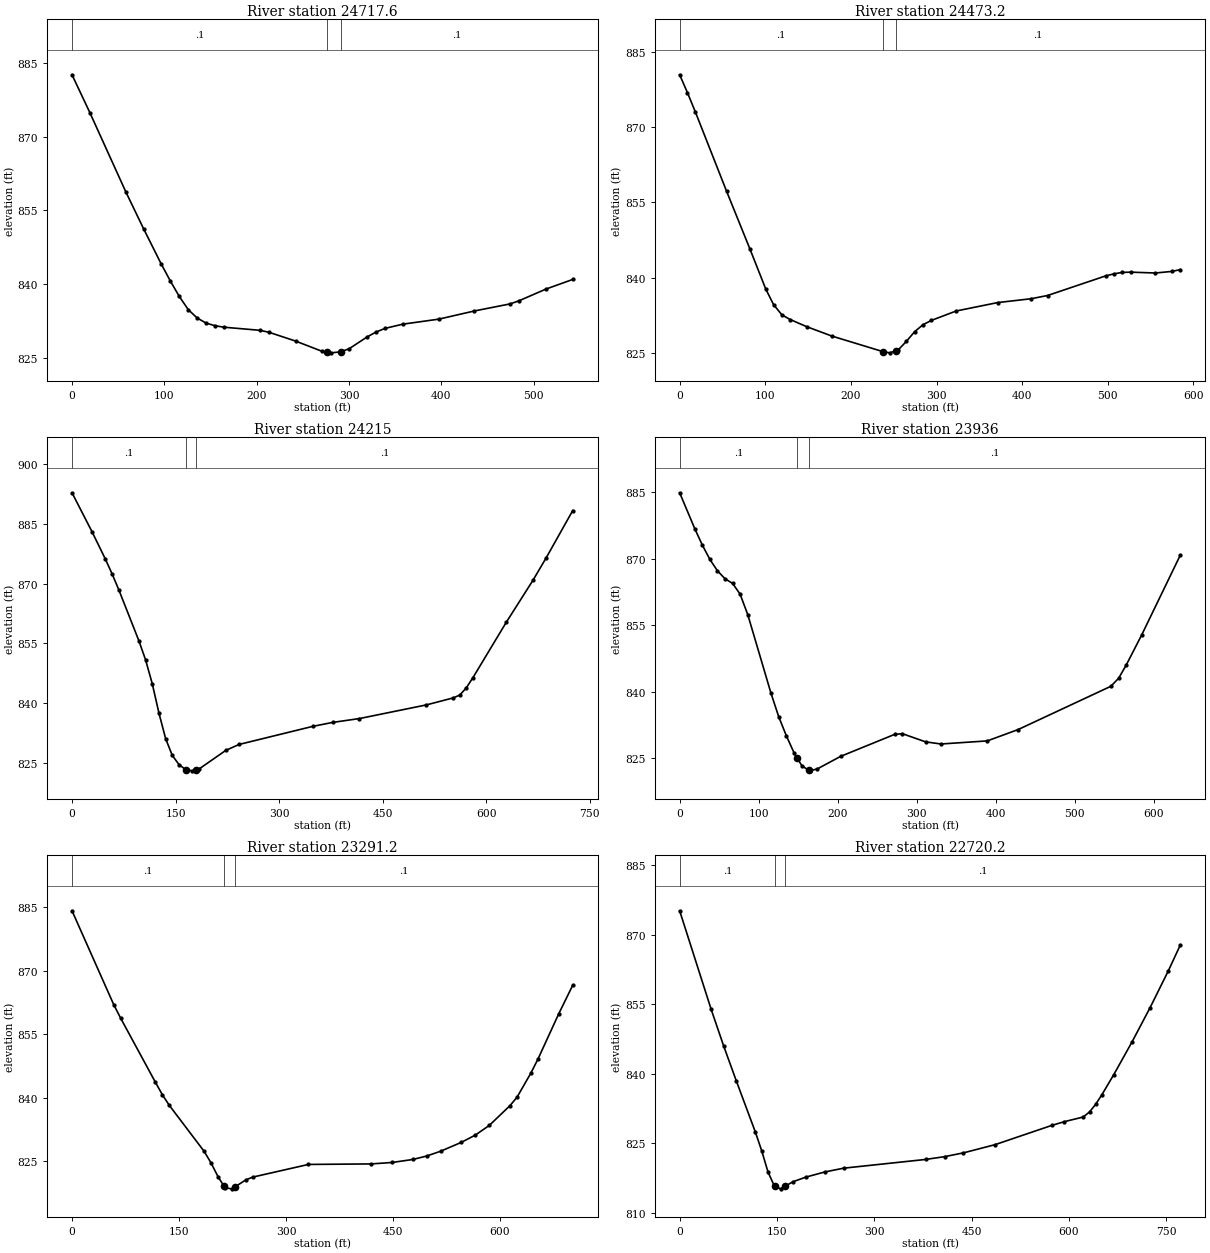
Type RM Length L Ch R = 1 ,24717.6 ,237.6,244.4,251.7
XS GIS Cut Line= 2
     1555625.552      323567.275     1555335.621      324025.608
#Sta/Elev= 30
       0  882.64    19.4   874.9    58.1  858.86    77.5  851.28    96.8  844.03
   106.5  840.63   116.2  837.48   125.9   834.8   135.6  833.09   145.3  832.05
     155  831.52   164.6  831.22   203.4  830.59   213.1   830.2   242.1   828.4
   271.2  826.28   276.1  826.14   280.8     826   291.1  826.21   300.2  826.84
   319.6  829.24   329.3  830.24     339  830.98   358.3  831.84   397.1  832.86
   435.8  834.53   474.5  835.97   484.2  836.61   513.3  838.99   542.3  840.95
#Mann= 3 , 0 , 0
       0      .1       0   276.1    .045       0   291.1      .1       0
Bank Sta=276.1,291.1
XS Rating Curve= 0 ,0
Exp/Cntr=0.3,0.1

Type RM Length L Ch R = 1 ,24473.2 ,260.6,258.2,255.5
XS GIS Cut Line= 3
     1555507.496      323506.511     1555424.163      323577.692
      1555023.99      323833.768
#Sta/Elev= 30
       0  880.47     9.1   876.9    18.3  873.07    54.8  857.23    82.2  845.65
   100.5  837.74   109.6  834.63   119.3  832.58     129  831.64   148.4  830.21
   177.5  828.35   237.4  825.23   245.3  824.99   252.4  825.39     255  825.54
   264.7  827.27   274.4  829.21   284.1   830.6   293.8  831.45   322.9  833.34
   371.4  835.02   410.2  835.78   429.6  836.43   497.4  840.34   507.1  840.75
   516.8  841.04   526.5  841.09   555.6  840.92     575  841.24   584.7   841.6
#Mann= 3 , 0 , 0
       0      .1       0   237.4    .045       0   252.4      .1       0
Bank Sta=237.4,252.4
XS Rating Curve= 0 ,0
Exp/Cntr=0.3,0.1

Type RM Length L Ch R = 1 ,24215   ,280.3,279,277.4
XS GIS Cut Line= 3
     1555375.273      323303.687     1554927.635      323642.796
     1554777.462        323707.9
#Sta/Elev= 30
       0  892.84      29  883.05    48.4  876.16    58.1  872.46    67.8  868.47
    96.8  855.71   106.5  850.92   116.2  844.93   125.9  837.54   135.6  831.12
   145.2  826.92   154.9  824.61   165.1  823.27   174.3  823.03   180.1  823.31
     184  823.49   222.7  828.16   242.1  829.66   348.6  834.19   377.6  835.19
   416.4  836.16   513.2  839.58   551.9  841.33   561.6  842.04   571.2  843.88
   580.8  846.45     629  860.32   667.5  870.82   686.8   876.5   725.3  888.38
#Mann= 3 , 0 , 0
       0      .1       0   165.1    .045       0   180.1      .1       0
Bank Sta=165.1,180.1
XS Rating Curve= 0 ,0
Exp/Cntr=0.3,0.1

Type RM Length L Ch R = 1 ,23936   ,648,644.8,641.2
XS GIS Cut Line= 3
     1555216.264      323088.976     1555146.819      323121.095
     1554735.361      323496.963
#Sta/Elev= 30
       0  884.86    19.1  876.78    28.7  873.07    38.3  869.83    47.8  867.28
    57.4  865.48      67  864.43    76.5  862.02    86.3  857.34   115.6  839.68
   125.4  834.37   135.2  830.02     145  826.16   148.7  825.08   154.7  823.32
   163.7  822.27   164.5  822.18   174.3  822.62   203.6  825.43     272  830.39
   281.8  830.56   311.2  828.72   330.7  828.23   389.4  828.93   428.5  831.49
   545.8  841.24   555.6  843.04   565.4  846.08   584.9  852.84   633.8  870.84
#Mann= 3 , 0 , 0
       0      .1       0   148.7    .045       0   163.7      .1       0
Bank Sta=148.7,163.7
XS Rating Curve= 0 ,0
Exp/Cntr=0.3,0.1

Type RM Length L Ch R = 1 ,23291.2 ,569.4,571,572.3
XS GIS Cut Line= 2
     1554773.035      322606.945     1554327.896      323150.001
#Sta/Elev= 30
       0   884.2    58.5  862.01    68.3  858.78     117  843.64   126.8  840.68
   136.5  838.18   185.3  827.32     195  824.58   204.8  821.32     213  819.14
   214.6  818.71   224.3  818.46     228  818.85   243.8  820.59   253.6  821.24
   331.6  824.23   419.4  824.35   448.6  824.69   477.9   825.4   497.4  826.22
   516.9  827.35   546.1  829.46   565.6  831.17   585.2  833.46   614.4  838.16
   624.2  840.16   643.7  845.89   653.4  849.13   682.7  859.89   702.2   866.6
#Mann= 3 , 0 , 0
       0      .1       0     213    .045       0     228      .1       0
Bank Sta=213,228
XS Rating Curve= 0 ,0
Exp/Cntr=0.3,0.1

Type RM Length L Ch R = 1 ,22720.2 ,363.7,376.3,388.6
XS GIS Cut Line= 3
     1554430.098      322200.727     1553998.559      322662.128
     1553943.004        322790.6
#Sta/Elev= 30
       0  875.12    48.6  853.87      68  845.93    87.5  838.41   116.6  827.49
   126.4  823.45   136.1  818.89   145.8  815.88   147.6  815.76   155.5  815.23
   162.6  815.81     175  816.78   194.4  817.75   223.5  818.86   252.7  819.68
     379  821.56   408.2  822.16   437.4  822.98     486  824.74   573.4  828.89
   592.9   829.7     622   830.7   631.8  831.81   641.1  833.44   650.4  835.42
   669.1  839.84   697.1  846.85   725.1  854.28   753.1  862.18   771.7  867.78
#Mann= 3 , 0 , 0
       0      .1       0   147.6    .045       0   162.6      .1       0
Bank Sta=147.6,162.6
XS Rating Curve= 0 ,0
Exp/Cntr=0.3,0.1

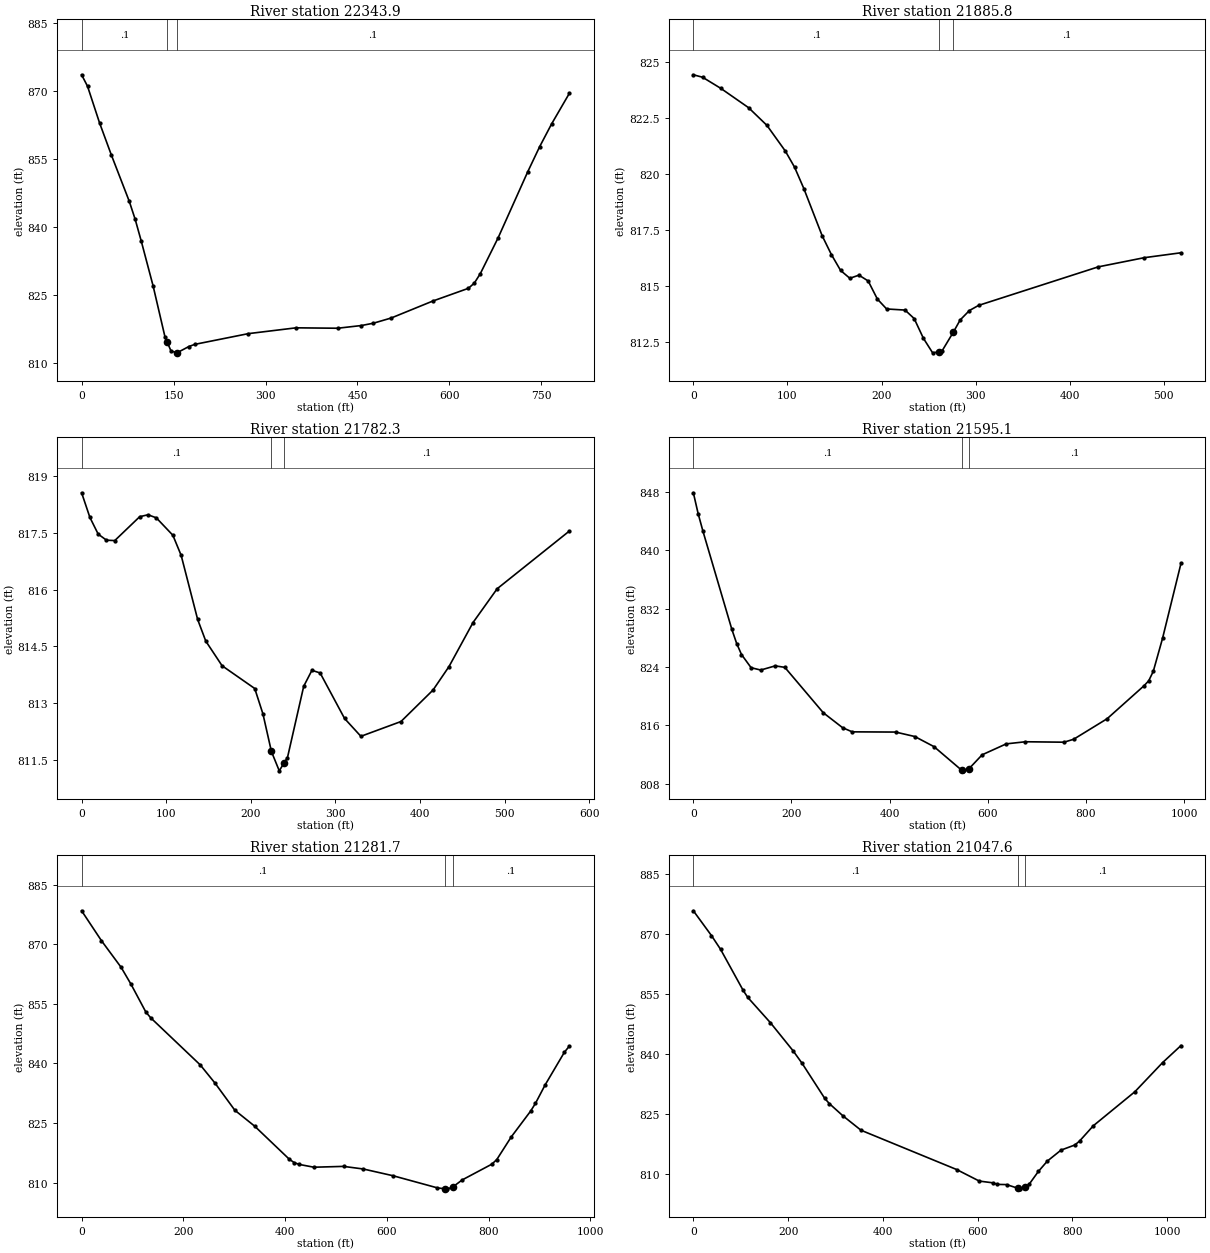
Type RM Length L Ch R = 1 ,22343.9 ,492.3,458,426.1
XS GIS Cut Line= 3
     1554357.211      321935.999     1553926.655      322056.008
     1553678.391      322300.799
#Sta/Elev= 30
       0  873.57     9.7  871.02    29.2  862.98    48.6  855.84    77.7  845.66
    87.4  841.66    97.2  836.91   116.6  826.99     136  815.72   139.9  814.49
   145.8  812.62   154.9  812.23   155.5   812.2   174.9  813.59   184.6  814.07
   272.1  816.44   349.8  817.72   417.8  817.63   456.6  818.23     476  818.74
   505.1  819.89   572.9  823.63     631  826.44   640.7   827.6   650.4  829.67
   679.4  837.56   727.8  852.16   747.2  857.69   766.6  862.69   795.6  869.45
#Mann= 3 , 0 , 0
       0      .1       0   139.9    .045       0   154.9      .1       0
Bank Sta=139.9,154.9
XS Rating Curve= 0 ,0
Exp/Cntr=0.3,0.1

Type RM Length L Ch R = 1 ,21885.8 ,98.8,103.5,104.7
XS GIS Cut Line= 3
     1553929.086      321382.686     1553941.238      321685.637
     1554017.392      321886.769
#Sta/Elev= 29
       0  824.43     9.8  824.32    29.3  823.82    58.7  822.96    78.2  822.17
    97.8  821.02   107.6   820.3   117.4  819.35   136.9  817.24   146.7   816.4
   156.5  815.69   166.3  815.34     176  815.48   185.8  815.22   195.6  814.41
   205.4  813.97     225  813.92   234.7  813.54   244.5  812.66   254.3  812.01
   261.4  812.06   264.1  812.08   276.4  812.94   283.6  813.48   293.4   813.9
   303.2  814.13   430.3  815.85   479.2  816.26   518.3  816.48
#Mann= 3 , 0 , 0
       0      .1       0   261.4    .045       0   276.4      .1       0
Bank Sta=261.4,276.4
XS Rating Curve= 0 ,0
Exp/Cntr=0.3,0.1

Type RM Length L Ch R = 1 ,21782.3 ,185.8,187.3,188.3
XS GIS Cut Line= 4
     1553814.936       321387.46     1553842.714      321511.939
     1553847.402      321714.544     1553940.501      321942.625
#Sta/Elev= 30
       0  818.55     9.8   817.9    19.6  817.46    29.4   817.3    39.2  817.29
    68.7  817.92    78.5  817.97    88.3  817.89   107.9  817.43   117.7   816.9
   137.2  815.21   146.8  814.64   166.1  813.99   204.7  813.39   214.4  812.72
   224.4  811.73   233.7  811.22   239.4  811.43   243.4  811.57   262.6  813.45
   272.3  813.87     282   813.8   310.9   812.6   330.2  812.13   377.6  812.52
   415.5  813.35   434.4  813.97   462.8  815.13   491.3  816.02   576.6  817.54
#Mann= 3 , 0 , 0
       0      .1       0   224.4    .045       0   239.4      .1       0
Bank Sta=224.4,239.4
XS Rating Curve= 0 ,0
Exp/Cntr=0.3,0.1

Type RM Length L Ch R = 1 ,21595.1 ,308.5,313.4,317.2
XS GIS Cut Line= 3
     1553685.795      321103.697     1553659.753       321937.03
     1553555.587      322058.558
#Sta/Elev= 30
       0  847.91     9.8  845.04    19.6  842.63    78.5  829.16    88.3  827.23
    98.1  825.72   117.7  823.91   137.3  823.59   166.8  824.16   186.4  823.96
   264.8  817.73   304.1  815.68   323.7  815.11     412  815.08   451.2  814.47
   490.4  813.08   546.7  809.85   549.3  809.76   561.7  810.05   588.5  811.96
   637.6  813.46   676.8  813.75   755.3  813.69   774.9  814.09   843.2  816.91
   918.5  821.44   927.9  822.11   937.3  823.42   956.1  827.93   993.8  838.25
#Mann= 3 , 0 , 0
       0      .1       0   546.7    .045       0   561.7      .1       0
Bank Sta=546.7,561.7
XS Rating Curve= 0 ,0
Exp/Cntr=0.3,0.1

Type RM Length L Ch R = 1 ,21281.7 ,214.7,234.1,249.3
XS GIS Cut Line= 4
     1553438.081      320913.467     1553433.625      321253.436
     1553351.594      321722.186     1553303.417      321856.301
#Sta/Elev= 30
       0  878.43    38.9  870.92    77.7  864.19    97.1  859.94   126.3  852.93
     136  851.47   233.1  839.65   262.3  835.04   301.1  828.24     340  824.24
     408  815.93   417.7  815.06   427.4  814.61   456.5   813.9   514.8  814.11
   553.7  813.45   611.9  811.76   699.3   808.7   713.9  808.47   718.8  808.46
   728.9  808.88   747.9   810.7   806.2  814.67   815.9  815.83   844.4  821.54
   882.4  828.02   891.9  829.97   910.9  834.61   948.9  842.86   958.4  844.36
#Mann= 3 , 0 , 0
       0      .1       0   713.9    .045       0   728.9      .1       0
Bank Sta=713.9,728.9
XS Rating Curve= 0 ,0
Exp/Cntr=0.3,0.1

Type RM Length L Ch R = 1 ,21047.6 ,598.8,596.3,592.8
XS GIS Cut Line= 5
     1553417.737      320920.227     1553392.997      321244.446
     1553327.893      321415.019     1553123.729      321589.374
     1553063.833      321835.467
#Sta/Elev= 30
       0  875.77    38.2  869.58    57.4  866.15   105.2  855.87   114.8  854.13
   162.6  847.81   210.4   840.8   229.5  837.66   277.3   828.9   286.9   827.6
   315.6  824.54     354  820.92   555.7  811.11   603.6  808.22   632.4  807.78
     642  807.39   661.2  807.34   685.8   806.4   689.9  806.28   700.8  806.66
   709.1  807.46   728.3  810.62   747.4  813.23   776.2  815.96   805.4  817.24
   815.2  818.21   844.4  822.05   932.1  830.55   990.5  837.82  1029.5   842.1
#Mann= 3 , 0 , 0
       0      .1       0   685.8    .045       0   700.8      .1       0
Bank Sta=685.8,700.8
XS Rating Curve= 0 ,0
Exp/Cntr=0.3,0.1

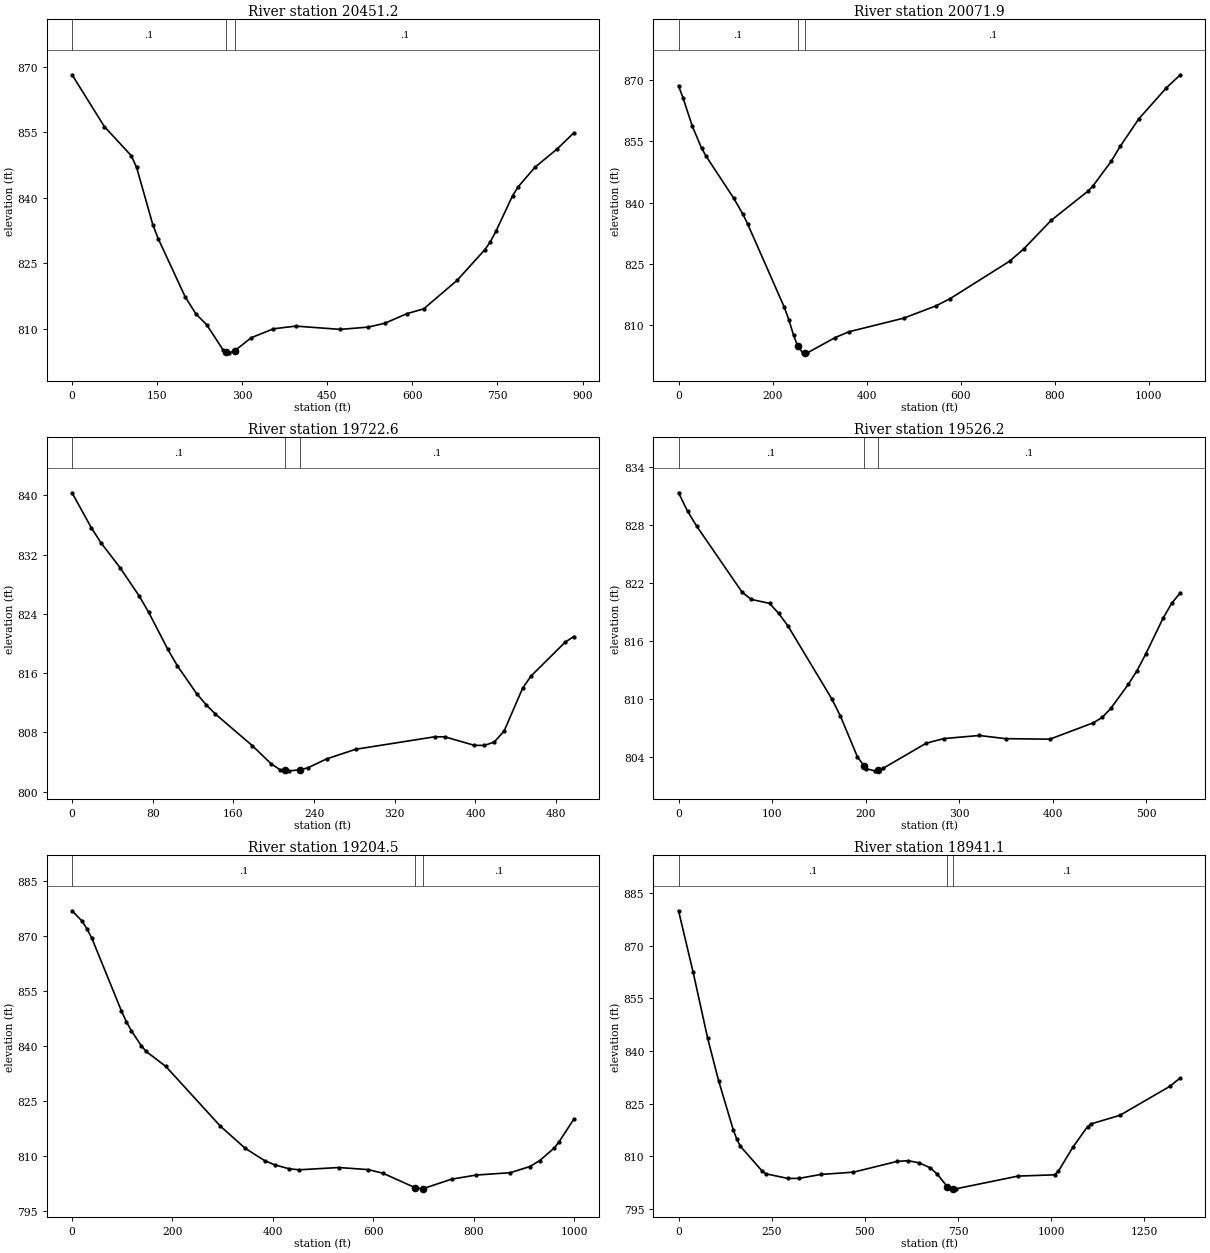
Type RM Length L Ch R = 1 ,20451.2 ,378,379.3,374.2
XS GIS Cut Line= 3
     1553085.535      320832.429      1552976.16      321032.082
     1552556.021       321537.29
#Sta/Elev= 30
       0  868.19    56.9  856.31   104.3  849.65   113.8  846.94   142.3  833.84
   151.8  830.63   199.2  817.32   218.2  813.38   237.5  810.83   266.9  804.97
     272  804.68   276.7  804.42     287  804.92   315.9  807.89   355.1  809.93
   394.4  810.55   472.8   809.8   521.9  810.32   551.3   811.2   590.5  813.41
   619.9   814.5   678.8  821.04   727.8  828.08   737.6  829.92   747.4  832.32
   776.8   840.5   786.7  842.53   816.1  846.97   855.3  851.19   884.7  854.88
#Mann= 3 , 0 , 0
       0      .1       0     272    .045       0     287      .1       0
Bank Sta=272,287
XS Rating Curve= 0 ,0
Exp/Cntr=0.3,0.1

Type RM Length L Ch R = 1 ,20071.9 ,340.1,349.3,358.3
XS GIS Cut Line= 3
     1552854.849      320613.245     1552399.749      321249.481
     1552325.944      321524.146
#Sta/Elev= 30
       0  868.63     9.8  865.58    29.3  858.72    48.9  853.38    58.7  851.36
   117.3  841.09   136.9  837.16   146.7  834.84   224.9  814.37   234.7  811.27
   244.4  807.58   253.2   804.9     264  803.23   268.2  803.23   273.8  803.22
   332.5  806.93   361.8  808.37   479.1  811.73   547.6  814.75   576.9  816.46
     704  825.68   733.4  828.62   792.1  835.66   870.5  842.83   880.3  843.99
   919.6   850.1   939.2  853.86   978.4  860.52  1037.2  868.14  1066.7  871.32
#Mann= 3 , 0 , 0
       0      .1       0   253.2    .045       0   268.2      .1       0
Bank Sta=253.2,268.2
XS Rating Curve= 0 ,0
Exp/Cntr=0.3,0.1

Type RM Length L Ch R = 1 ,19722.6 ,196.3,196.5,196.3
XS GIS Cut Line= 5
     1552645.396      320511.841     1552521.687      320560.652
     1552411.926      320627.626     1552241.653      320675.033
       1552185.5      320656.112
#Sta/Elev= 30
       0  840.34      19  835.64    28.5  833.62    47.5  830.25    66.5  826.42
      76   824.2      95  819.19   104.5  816.97   123.5  813.24     133  811.72
   142.2  810.47   178.9  806.19   197.3  803.77   206.5  802.94   211.5  802.87
   215.6  802.81   226.5  802.95     234  803.23   252.4  804.42   281.2  805.72
   359.8  807.41   369.6   807.4     399  806.25   408.9  806.24   418.7   806.7
   428.5   808.2   446.8  813.96   455.2  815.62   489.1  820.19   497.6  820.94
#Mann= 3 , 0 , 0
       0      .1       0   211.5    .045       0   226.5      .1       0
Bank Sta=211.5,226.5
XS Rating Curve= 0 ,0
Exp/Cntr=0.3,0.1

Type RM Length L Ch R = 1 ,19526.2 ,349.1,321.7,290.7
XS GIS Cut Line= 5
     1552548.217      320365.411     1552416.582      320400.411
     1552306.821      320467.386     1552179.378      320502.868
     1552177.557      320642.321
#Sta/Elev= 30
       0  831.38     9.7  829.46    19.5  827.91    68.1  821.07    77.8  820.34
    97.3  819.93     107   818.9   116.8  817.62   163.8  810.05     173  808.28
   191.3  804.03   198.2  803.12   200.5  802.82   209.7  802.59   213.2  802.69
   218.9  802.86   264.8  805.45   283.7  805.93   321.5  806.25   349.8  805.92
   397.1  805.87   443.6  807.57   452.9  808.12   462.2  809.06   480.8  811.53
   490.1  812.95   499.4  814.66     518  818.39   527.2  819.93   536.5  821.03
#Mann= 3 , 0 , 0
       0      .1       0   198.2    .045       0   213.2      .1       0
Bank Sta=198.2,213.2
XS Rating Curve= 0 ,0
Exp/Cntr=0.3,0.1

Type RM Length L Ch R = 1 ,19204.5 ,264,263.4,259.3
XS GIS Cut Line= 3
     1552650.874      320002.524     1552105.301      320227.133
     1552158.469      320632.949
#Sta/Elev= 30
       0  876.94    19.7  874.16    29.5  872.06    39.3  869.49    98.3  849.65
   108.2  846.69     118  844.29   137.7  840.18   147.5  838.61   186.8  834.52
     295   818.3   344.2  812.28   383.5  808.85   403.2  807.73   432.7  806.62
   452.3  806.36     531  806.98     590  806.41   619.2  805.42   683.7  801.45
   697.2  801.17   698.7  801.21   755.7   803.8   804.4  804.92   872.6  805.57
   911.6  807.24   931.1  808.84   960.3  812.31     970  814.03   999.3  820.16
#Mann= 3 , 0 , 0
       0      .1       0   683.7    .045       0   698.7      .1       0
Bank Sta=683.7,698.7
XS Rating Curve= 0 ,0
Exp/Cntr=0.3,0.1

Type RM Length L Ch R = 1 ,18941.1 ,590.9,588.6,581.7
XS GIS Cut Line= 4
     1551467.843      319753.833     1551834.162      320120.152
     1551966.107      320724.319     1551920.968       320929.18
#Sta/Elev= 30
       0  879.92    39.1  862.46    78.2  843.58   107.5  831.54   146.6   817.6
   156.4  814.86   166.2  812.82   224.8  805.74   234.6  805.01   293.2   803.7
   322.6   803.7   381.2  804.82   469.2  805.48   586.8  808.55   616.2  808.74
   645.7  808.12   675.1  806.73   694.7  804.86     721  801.33     736  800.74
   743.8  800.73   910.7  804.36  1008.8  804.72  1018.7   805.7  1057.9  812.58
  1097.2  818.44    1107  819.23  1184.1  821.67  1317.6  829.89  1346.2  832.33
#Mann= 3 , 0 , 0
       0      .1       0     721    .045       0     736      .1       0
Bank Sta=721,736
XS Rating Curve= 0 ,0
Exp/Cntr=0.3,0.1

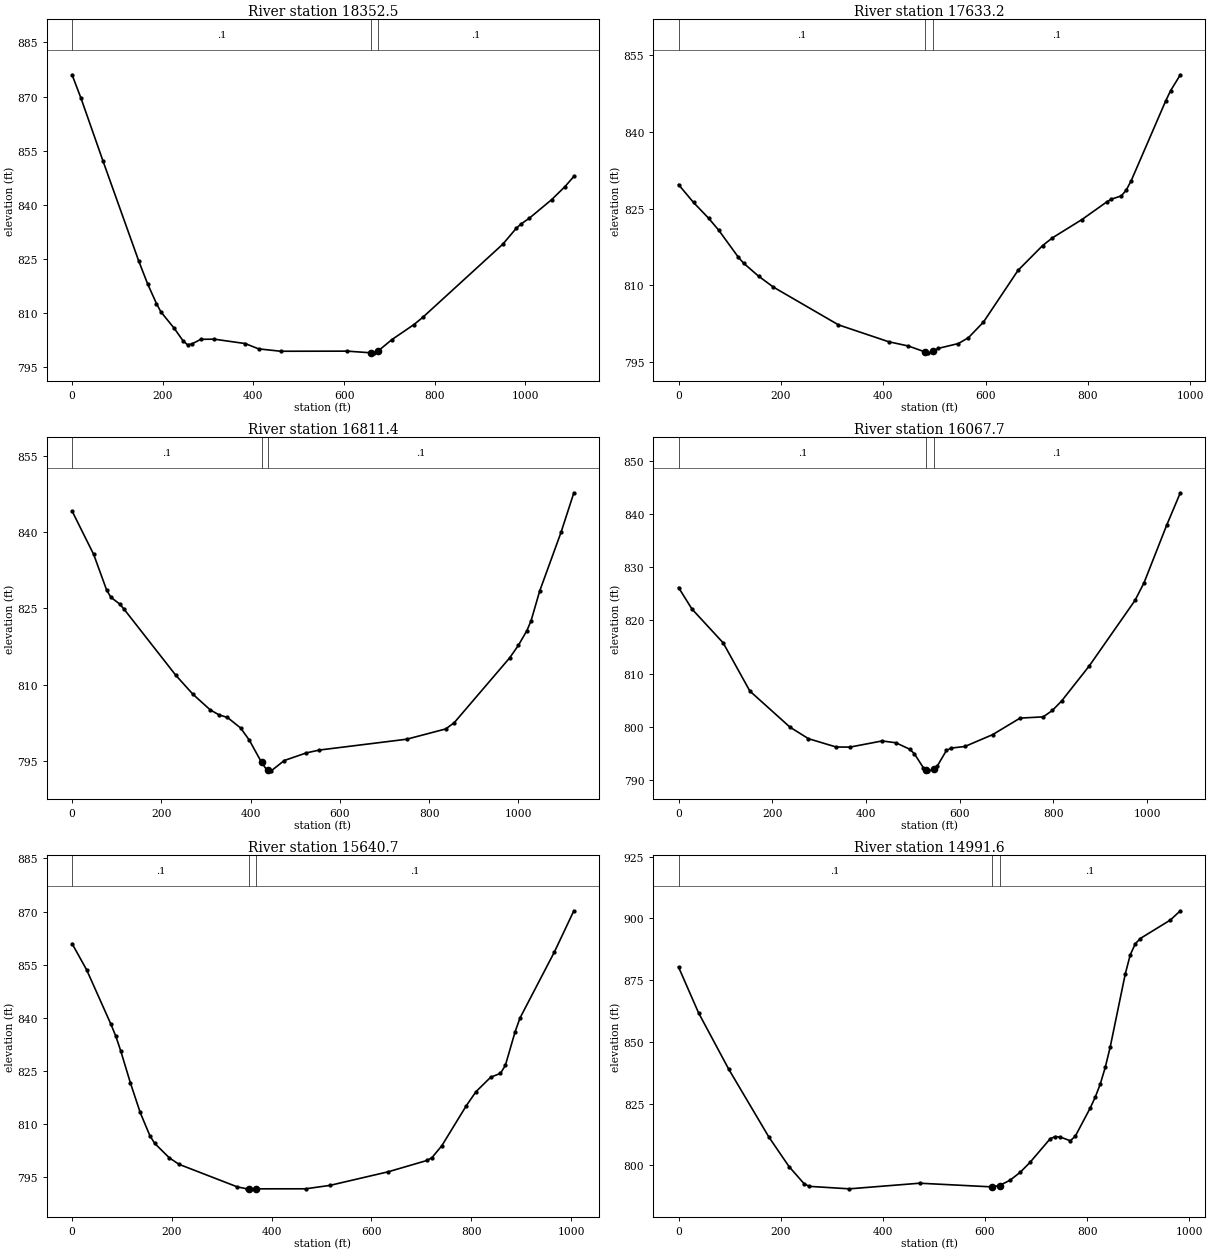
Type RM Length L Ch R = 1 ,18352.5 ,719.6,719.3,713.7
XS GIS Cut Line= 2
     1551159.683       320039.77     1551747.791       320977.27
#Sta/Elev= 30
       0  876.03    19.6  869.56    68.6     852   146.9  824.47   166.5  818.13
   186.1  812.64   195.9  810.33   225.3  805.78   244.8  802.31   254.6  801.22
   264.4  801.46     284  802.73   313.4  802.77     382  801.55   411.3  800.08
   460.3  799.42   607.2  799.45   658.8  798.99     666  798.98   673.8  799.37
   705.2  802.63   754.1  806.82   773.7  808.84     950  829.09   979.4  833.45
   989.2  834.59  1008.8  836.32  1057.7  841.43  1087.1  845.05  1106.7  847.86
#Mann= 3 , 0 , 0
       0      .1       0   658.8    .045       0   673.8      .1       0
Bank Sta=658.8,673.8
XS Rating Curve= 0 ,0
Exp/Cntr=0.3,0.1

Type RM Length L Ch R = 1 ,17633.2 ,791.8,821.8,842.6
XS GIS Cut Line= 3
     1550617.148      320517.201     1551018.624       320983.78
     1551144.492      321326.662
#Sta/Elev= 30
       0  829.73    29.3  826.23    58.6  823.17    78.2  820.86   117.2  815.49
     127  814.38   156.3  811.83   185.6  809.67   312.6   802.3   410.4  799.01
   449.4  798.16   482.3  796.99   488.5  796.83   497.3  797.16   508.1  797.71
   547.1  798.65   566.7   799.8     596  802.84   663.6  812.96   711.6   817.8
   730.9  819.32   788.6   822.9   836.6  826.31   846.2  826.89   865.4  827.51
     875  828.64   884.7  830.47     952  846.04   961.6  848.06   980.8   851.2
#Mann= 3 , 0 , 0
       0      .1       0   482.3    .045       0   497.3      .1       0
Bank Sta=482.3,497.3
XS Rating Curve= 0 ,0
Exp/Cntr=0.3,0.1

Type RM Length L Ch R = 1 ,16811.4 ,755.2,743.7,733.2
XS GIS Cut Line= 4
     1550578.103      320461.606     1550558.572      320809.262
     1550356.749      321201.189     1550384.961       321535.39
#Sta/Elev= 30
       0  844.14    48.4  835.62    77.4  828.63      87   827.2   106.4   825.9
   116.1  824.91   232.1  811.92   270.8  808.16   309.5   805.1   328.9  804.13
   348.2   803.6   377.6  801.54   397.2  799.14   424.6  794.78   436.4  793.29
   439.6  793.23   446.2  793.12   475.6  795.15   524.5  796.63   553.9   797.2
   749.9  799.33     837  801.34   856.1  802.55   980.7  815.32   999.9  817.74
    1019  820.62  1028.6  822.61  1047.8  828.42  1095.7  839.96  1124.4  847.72
#Mann= 3 , 0 , 0
       0      .1       0   424.6    .045       0   439.6      .1       0
Bank Sta=424.6,439.6
XS Rating Curve= 0 ,0
Exp/Cntr=0.3,0.1

Type RM Length L Ch R = 1 ,16067.7 ,427.1,426.9,431.5
XS GIS Cut Line= 4
     1550125.495       320502.39     1550084.018      320736.726
     1550235.807      321427.679     1550294.766      321538.848
#Sta/Elev= 30
       0   826.2    28.6  822.16    95.2   815.8   152.3  806.72     238  799.93
   277.3  797.77   336.2  796.21   365.7  796.18   434.5  797.34     464     797
   493.4  795.79   503.3  794.95   522.9  792.27   529.3  791.91   532.7  791.72
   544.3  792.01   552.4  792.63     572  795.57   581.9     796   611.3   796.3
   670.3  798.52   729.2  801.64   778.4  801.87     798  803.07   817.7  804.85
   876.6  811.43   974.4  823.77   993.8  827.11  1042.2  837.95  1071.2  844.02
#Mann= 3 , 0 , 0
       0      .1       0   529.3    .045       0   544.3      .1       0
Bank Sta=529.3,544.3
XS Rating Curve= 0 ,0
Exp/Cntr=0.3,0.1

Type RM Length L Ch R = 1 ,15640.7 ,647.9,649.2,644.1
XS GIS Cut Line= 3
     1549744.753      320623.537     1549942.235      321307.131
     1549968.277        321600.1
#Sta/Elev= 30
       0  860.93    29.2  853.51      78  838.09    87.7  834.74    97.5  830.62
     117  821.51   136.5   813.2     156  806.61   165.7  804.44   194.9  800.36
   214.4  798.53   331.4  792.14   350.9   791.6   353.8   791.6   368.8   791.6
   467.9  791.61   516.6  792.57   633.6  796.42   711.6  799.63   721.4  800.45
     741  803.77     790  815.07   809.6  819.08     839  823.15   858.6  824.25
   868.4  826.49     888  836.03   897.8  839.91   966.4  858.48  1005.7  870.21
#Mann= 3 , 0 , 0
       0      .1       0   353.8    .045       0   368.8      .1       0
Bank Sta=353.8,368.8
XS Rating Curve= 0 ,0
Exp/Cntr=0.3,0.1

Type RM Length L Ch R = 1 ,14991.6 ,1231.3,1212.1,1188.5
XS GIS Cut Line= 3
      1549412.07      320745.427     1549520.577      321455.062
     1549448.719      321709.599
#Sta/Elev= 30
       0  880.33    39.3  861.73    98.3  838.95     177  811.43   216.4   799.5
   245.8  792.58   255.7  791.51   334.4   790.5     472  792.78   613.5  791.29
   628.5  791.85     649  793.99   668.7  797.15   688.4  801.28   727.7  810.81
   737.5  811.68   747.3  811.49   766.9  809.98   776.7  811.79     806  823.24
   815.8  827.63   825.6   832.9   835.4  839.68   845.2  848.02   874.6  877.53
   884.4   885.3   894.2  889.74     904  891.89   962.8  899.36   982.4  903.12
#Mann= 3 , 0 , 0
       0      .1       0   613.5    .045       0   628.5      .1       0
Bank Sta=613.5,628.5
XS Rating Curve= 0 ,0
Exp/Cntr=0.3,0.1

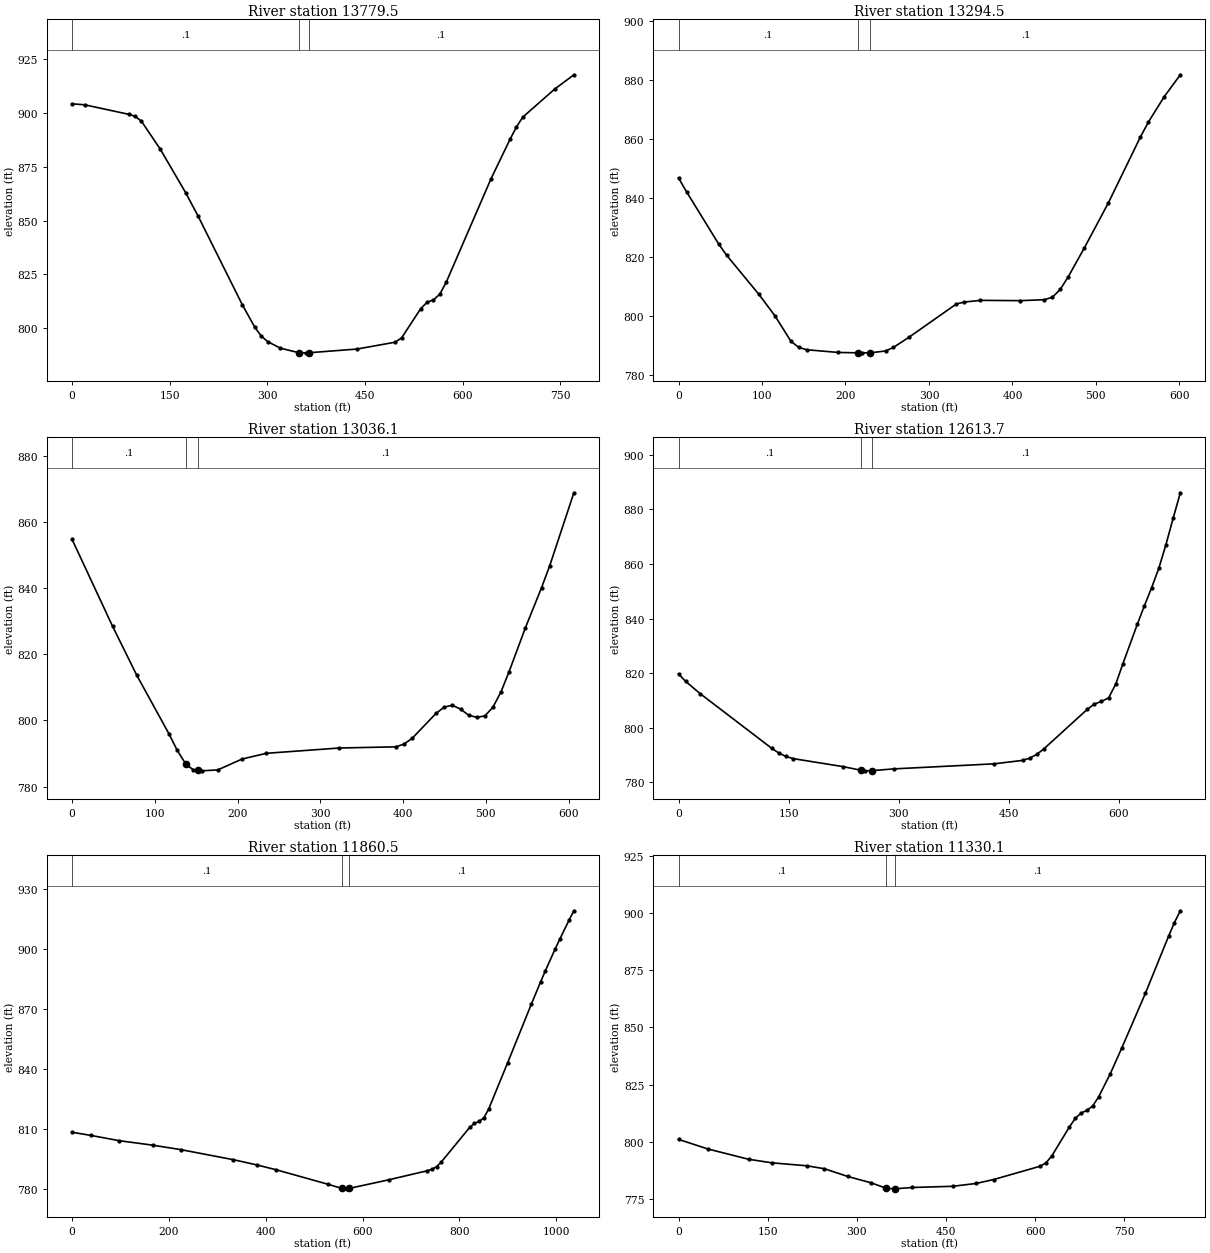
Type RM Length L Ch R = 1 ,13779.5 ,524.9,485,495
XS GIS Cut Line= 3
     1548684.355      321522.227      1548971.17      321569.718
     1549399.773      321786.732
#Sta/Elev= 30
       0  904.25    19.4   903.8    87.2  899.37    96.9  898.44   106.6  896.17
   135.7  883.12   174.4  863.06   193.8  852.03   261.6  810.94     281  800.39
   290.7  796.43   300.5  793.82   320.1  790.77   348.4  788.67   359.4   788.6
   363.4  788.63   437.8  790.36   496.6  793.55   506.4  795.56   535.8  809.14
   545.6   812.1   555.4  813.18   565.2   815.9     575  821.42   643.7  869.38
   673.1  887.82   682.9  893.54   692.7   898.1   741.7  911.11   771.1  917.74
#Mann= 3 , 0 , 0
       0      .1       0   348.4    .045       0   363.4      .1       0
Bank Sta=348.4,363.4
XS Rating Curve= 0 ,0
Exp/Cntr=0.3,0.1

Type RM Length L Ch R = 1 ,13294.5 ,187.9,258.4,277.6
XS GIS Cut Line= 4
     1548757.195      321750.925     1548795.172      321870.282
     1548888.488      322055.829     1549156.556      322062.404
#Sta/Elev= 30
       0  846.78     9.6  842.08    48.2  824.29    57.8  820.47    96.4  807.21
   115.6  799.92   134.7  791.31   144.1  789.23   153.6  788.45   191.3  787.53
   214.8  787.41   219.7   787.4   229.8  787.42     248  788.03   257.4  789.24
   276.3  792.74   332.9  804.01   342.5  804.65   361.7  805.22   409.6  805.12
   438.3  805.44   447.9  806.29   457.4     809     467  813.31   486.2  823.07
   514.9  838.32   553.2  860.65   562.8  865.73   581.9  874.42   601.1  881.81
#Mann= 3 , 0 , 0
       0      .1       0   214.8    .045       0   229.8      .1       0
Bank Sta=214.8,229.8
XS Rating Curve= 0 ,0
Exp/Cntr=0.3,0.1

Type RM Length L Ch R = 1 ,13036.1 ,427.3,422.4,417.8
XS GIS Cut Line= 2
      1548647.82      321731.176      1548500.25      322319.284
#Sta/Elev= 30
       0  854.73    48.9  828.48    78.2  813.64   117.4  795.79   127.1  790.92
   137.6  786.75   146.7  785.02   152.6  784.86   156.5  784.75     176  785.03
   205.4  788.32   234.7  790.05   322.7  791.65   391.2  792.01     401  792.83
   410.8  794.55   440.1   802.2   449.9  804.05   459.6  804.58   469.4   803.4
   479.2  801.57     489  800.93   498.8  801.36   508.5  803.98   518.3  808.65
   528.1  814.78   547.7  827.97   567.2  840.09     577  846.66   606.3  868.82
#Mann= 3 , 0 , 0
       0      .1       0   137.6    .045       0   152.6      .1       0
Bank Sta=137.6,152.6
XS Rating Curve= 0 ,0
Exp/Cntr=0.3,0.1

Type RM Length L Ch R = 1 ,12613.7 ,756.3,753.2,733.2
XS GIS Cut Line= 2
     1548202.941      321570.803       1548176.9      322254.397
#Sta/Elev= 30
       0  819.66     9.8  816.97    29.3  812.53     127  792.49   136.8  790.74
   146.6  789.49   156.4   788.7   224.8  785.75   248.8  784.44   254.1  784.23
   263.8   784.3   293.2  784.94     430  786.79   469.1  788.06   478.9  788.89
   488.6  790.29   498.4  792.35     557  806.69   566.8  808.68   576.6  809.65
   586.4  810.96   596.1  816.02   605.9  823.52   625.4  837.85   635.2  844.74
     645  851.31   654.8  858.42   664.5  867.06   674.3   876.7   684.1  886.04
#Mann= 3 , 0 , 0
       0      .1       0   248.8    .045       0   263.8      .1       0
Bank Sta=248.8,263.8
XS Rating Curve= 0 ,0
Exp/Cntr=0.3,0.1

Type RM Length L Ch R = 1 ,11860.5 ,532.9,530.4,526
XS GIS Cut Line= 2
     1547528.625      321446.834     1547763.868      322456.382
#Sta/Elev= 30
       0  808.36    39.1  806.77    97.8  804.13   166.2  801.92   224.9  799.66
   332.5  794.68   381.4  792.05   420.5  789.68   528.1   782.4   556.6  780.32
   567.2  780.07   571.6  780.24   655.2  784.64   733.4  789.09   743.2  789.79
     753  791.17   762.8  793.51   821.4  810.78   831.2  812.77     841  813.78
   850.8  815.62   860.6  819.97   899.7  843.05   948.6  872.29   968.1  883.66
   977.9  889.17   997.5  899.76  1007.3   904.8  1026.8  914.49  1036.6  919.09
#Mann= 3 , 0 , 0
       0      .1       0   556.6    .045       0   571.6      .1       0
Bank Sta=556.6,571.6
XS Rating Curve= 0 ,0
Exp/Cntr=0.3,0.1

Type RM Length L Ch R = 1 ,11330.1 ,329.7,340.9,353.9
XS GIS Cut Line= 2
     1547132.783      321734.224     1547470.795      322507.869
#Sta/Elev= 30
       0  801.08    49.1  796.91   117.8  792.39   157.1  790.83     216  789.54
   245.4  788.25   284.7  784.87     324   782.1     349  779.75   363.2  779.46
     364  779.47   392.7  780.05   461.4  780.57   500.7  781.81   530.1  783.52
   608.6  789.36   618.5  790.86   628.3  793.97   657.7  806.53   667.6  810.28
   677.4  812.62   687.2  813.75     697  815.75   706.8  819.64   726.5   829.8
   746.1  841.23   785.4  864.86   824.6  889.94   834.4  895.89   844.3  901.02
#Mann= 3 , 0 , 0
       0      .1       0     349    .045       0     364      .1       0
Bank Sta=349,364
XS Rating Curve= 0 ,0
Exp/Cntr=0.3,0.1