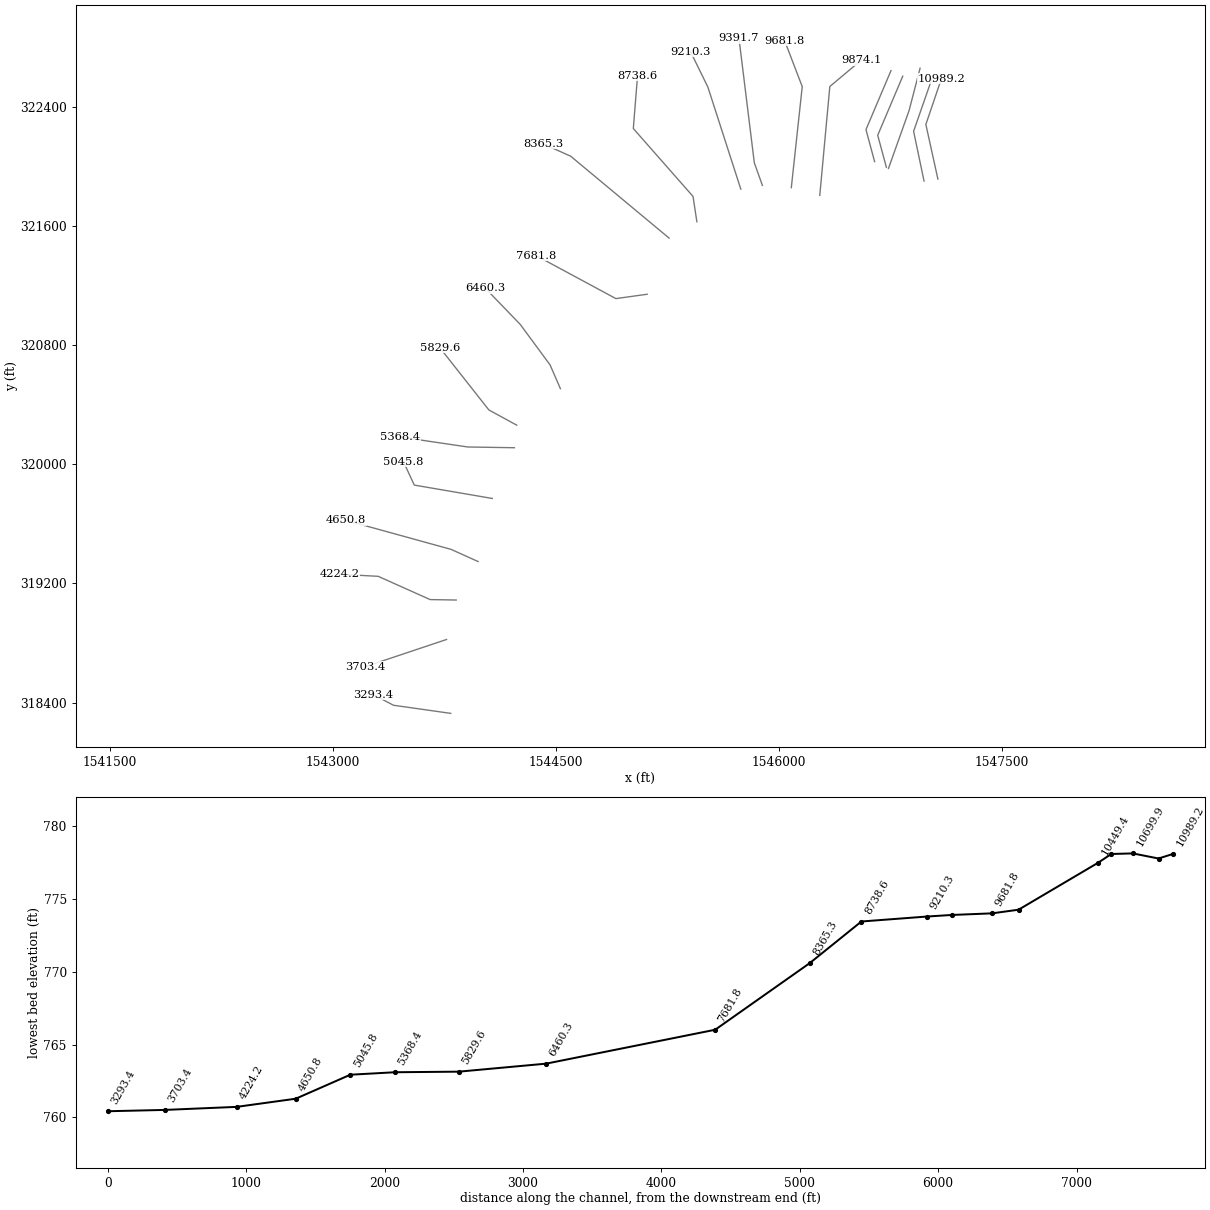
HEC-RAS study MCKIMCRK.prj: MCKIMCRK

--- MCKIMCRK.g02 (geometry) --- (continued)

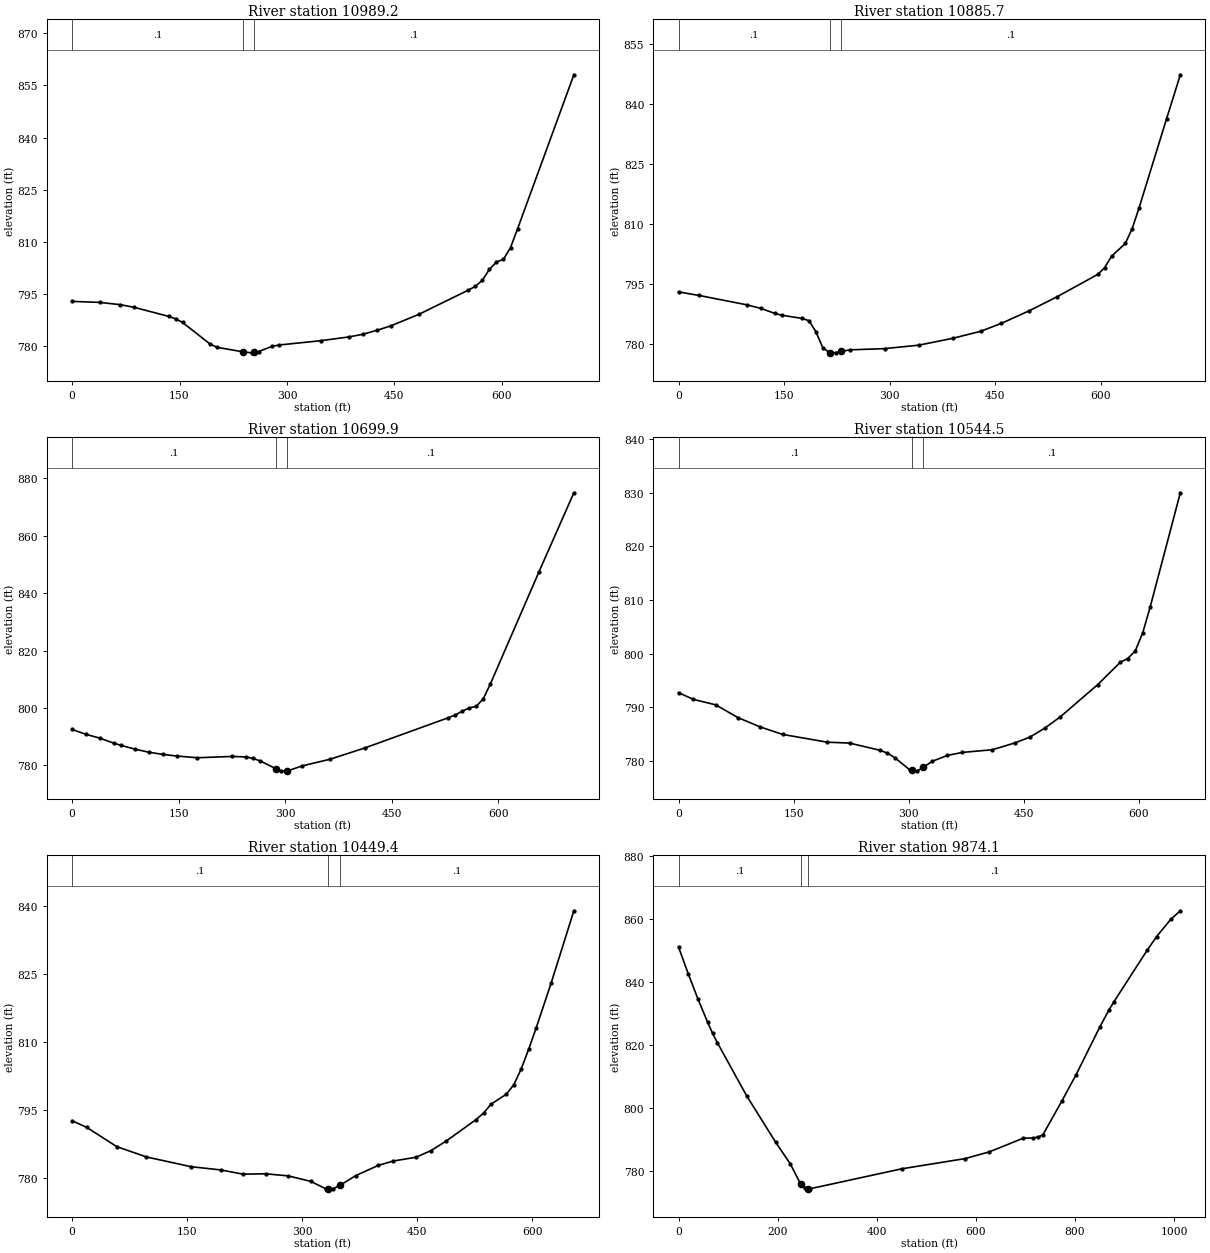
Type RM Length L Ch R = 1 ,10989.2 ,96.6,103.4,195.6
XS GIS Cut Line= 3
     1547071.903      321917.818     1546990.814      322285.179
     1547095.341      322592.297
#Sta/Elev= 30
       0  792.89    38.6   792.6    67.5  791.94    86.8  791.18     135  788.57
   144.7  787.88   154.3  786.83   192.9  780.59   202.6  779.68   239.2  778.37
   250.8   778.1   254.2  778.23   260.4  778.48   279.7  779.99   289.4  780.36
   347.3  781.59     386  782.66   405.7  783.42   425.4  784.56     445  785.85
   484.3  789.18   553.2  796.12     563  797.21   572.8  798.95   582.6  802.07
   592.5   804.2   602.3     805   612.2  808.36     622  813.75   700.6  858.03
#Mann= 3 , 0 , 0
       0      .1       0   239.2    .045       0   254.2      .1       0
Bank Sta=239.2,254.2
XS Rating Curve= 0 ,0
Exp/Cntr=0.3,0.1

Type RM Length L Ch R = 1 ,10885.7 ,201.9,185.8,79.7
XS GIS Cut Line= 3
     1546978.587       321904.97     1546908.349      322239.172
     1547030.671      322589.866
#Sta/Elev= 30
       0  793.01    29.3  792.12    97.6  789.76   117.1  788.88   136.6  787.65
   146.4  787.19   175.6  786.39   185.4  785.81   195.1  783.06   204.9   779.1
   214.7  777.79   215.3  777.79   224.4  777.87   230.3  778.14   243.9  778.54
   292.7  778.84   341.5  779.71   390.4  781.45   429.5  783.19   458.8  785.16
   497.9  788.27     537  791.72   595.6  797.38   605.4  799.08   615.2  801.92
   634.7   805.1   644.5  808.81   654.3  814.01   693.4  836.28   712.9  847.24
#Mann= 3 , 0 , 0
       0      .1       0   215.3    .045       0   230.3      .1       0
Bank Sta=215.3,230.3
XS Rating Curve= 0 ,0
Exp/Cntr=0.3,0.1

Type RM Length L Ch R = 1 ,10699.9 ,156.8,155.4,154.1
XS GIS Cut Line= 3
     1546739.424      321989.481     1546877.705      322377.675
     1546951.924      322662.832
#Sta/Elev= 30
       0  792.55    19.6  790.86    39.2  789.53    58.9  787.76    68.7  787.04
    88.3  785.72   107.9  784.64   127.6  783.87   147.2   783.3   176.6   782.7
   225.7  783.16   245.3  782.97   255.1  782.44   264.9   781.6   287.9  778.78
   294.4  778.14   302.9  778.17   304.2  778.17   323.8  779.85     363  782.16
   412.1  786.09     530  796.65   539.8  797.61   549.6  798.94   559.4  800.04
   569.2  800.62   579.1  803.22   588.9  808.29   657.6  847.47   706.7  874.99
#Mann= 3 , 0 , 0
       0      .1       0   287.9    .045       0   302.9      .1       0
Bank Sta=287.9,302.9
XS Rating Curve= 0 ,0
Exp/Cntr=0.3,0.1

Type RM Length L Ch R = 1 ,10544.5 ,93.5,95,94.8
XS GIS Cut Line= 3
     1546725.144      321997.332     1546666.984      322212.609
     1546835.387      322609.311
#Sta/Elev= 30
       0   792.7    19.4  791.44    48.5  790.42    77.6  788.03   106.6  786.29
   135.7   784.9   193.9  783.45     223  783.28   262.2  781.95     272  781.43
   281.8  780.56   301.4  778.28   303.9  778.23   311.2   778.1   318.9  778.75
   330.7  779.88   350.3  780.98   369.9  781.54   409.1  782.04   438.5  783.32
   458.1  784.41   477.7  786.11   497.2  788.14   546.2  794.18   575.6  798.35
   585.4  799.07   595.2  800.47     605  803.87   614.8  808.74     654  830.02
#Mann= 3 , 0 , 0
       0      .1       0   303.9    .045       0   318.9      .1       0
Bank Sta=303.9,318.9
XS Rating Curve= 0 ,0
Exp/Cntr=0.3,0.1

Type RM Length L Ch R = 1 ,10449.4 ,569.1,575.3,582.2
XS GIS Cut Line= 3
     1546646.151      322035.092     1546587.991       322250.37
     1546756.394      322647.071
#Sta/Elev= 30
       0  792.56    19.4  791.07    58.2  786.84      97  784.55   155.1   782.4
   193.9  781.68     223  780.74   252.4  780.83   281.8  780.36   311.2  779.15
   330.7   777.5   334.1  777.51   340.5  777.54   349.1  778.27   369.9  780.44
   399.3   782.7   418.9  783.66   448.3  784.49   467.9  785.97   487.4  788.04
   526.6  792.83   536.4  794.28   546.2  796.25   565.8  798.41   575.6   800.5
   585.4  804.02   595.2  808.43     605  813.15   624.6  823.13     654  839.01
#Mann= 3 , 0 , 0
       0      .1       0   334.1    .045       0   349.1      .1       0
Bank Sta=334.1,349.1
XS Rating Curve= 0 ,0
Exp/Cntr=0.3,0.1

Type RM Length L Ch R = 1 ,9874.1  ,192.6,192.3,191.9
XS GIS Cut Line= 3
     1546277.184      321808.057     1546344.866       322540.07
     1546557.496      322718.455
#Sta/Elev= 30
       0  851.13    19.6  842.63    39.2  834.61    58.8  827.18    68.6  823.75
    78.4  820.71   137.2  803.92     196  789.08   225.4  782.25     245  776.22
     247  775.88   254.8  774.56     262  774.35   264.6  774.27   450.9  780.65
   578.3  783.88   627.3  786.03   695.9  790.38   715.5  790.44   725.3  790.73
   735.1  791.38   773.4  802.12   802.1  810.48     850  825.66   869.1  831.26
   878.7  833.75   945.7  850.09   964.8  854.46   993.5  859.96  1012.7  862.66
#Mann= 3 , 0 , 0
       0      .1       0     247    .045       0     262      .1       0
Bank Sta=247,262
XS Rating Curve= 0 ,0
Exp/Cntr=0.3,0.1

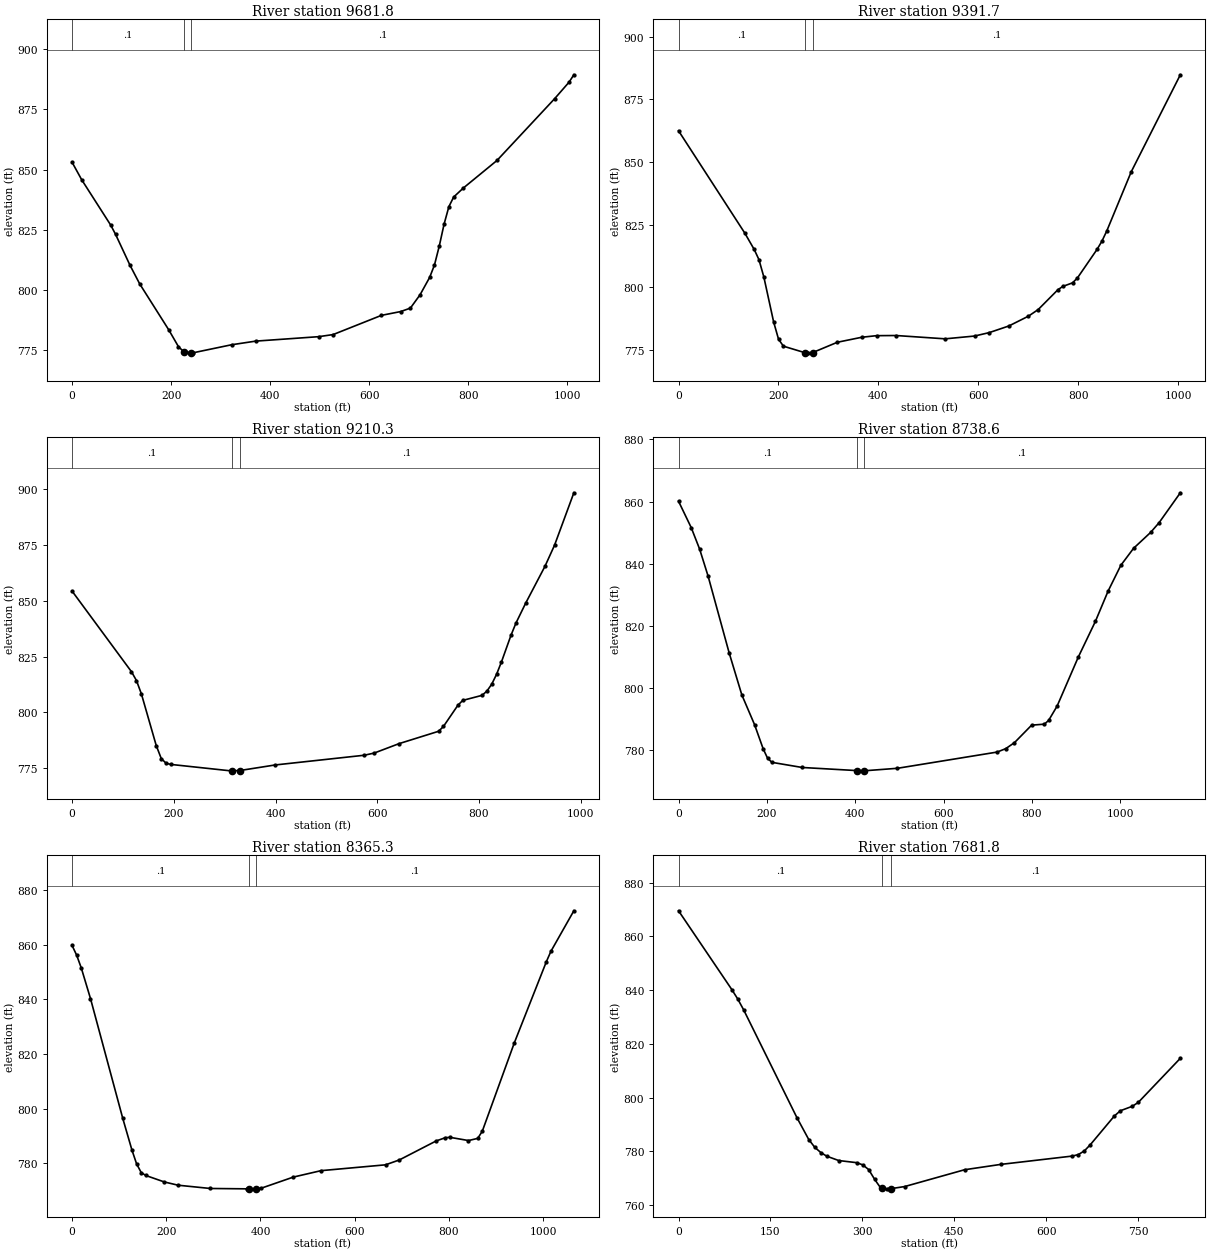
Type RM Length L Ch R = 1 ,9681.8  ,284.4,290.1,295.6
XS GIS Cut Line= 3
     1546085.778      321860.141     1546159.276      322539.418
     1546041.003      322847.578
#Sta/Elev= 30
       0  853.05    19.5  845.77    78.1  826.96    87.8  823.17   117.1  810.28
   136.6   802.6   195.2  783.57   214.7  776.63   225.1  774.54   240.1  774.03
     244  774.02   322.1  777.37   370.9  778.88   497.8  780.72   527.1  781.59
   624.7  789.56   663.7  791.14   683.2  792.57   702.7  798.09   722.1   805.3
   731.8  810.44   741.5  818.28   751.2  827.36   760.9  834.63   770.6  838.63
     790  842.34     858  853.78   974.5  879.41  1003.6  886.26  1013.3  889.32
#Mann= 3 , 0 , 0
       0      .1       0   225.1    .045       0   240.1      .1       0
Bank Sta=225.1,240.1
XS Rating Curve= 0 ,0
Exp/Cntr=0.3,0.1

Type RM Length L Ch R = 1 ,9391.7  ,177.6,181.5,185.8
XS GIS Cut Line= 3
     1545891.241      321875.602     1545836.987      322027.077
     1545733.688      322863.883
#Sta/Elev= 30
       0   862.5   132.5  821.71   151.4  815.16   160.9   811.1   170.7  804.18
   190.3  786.23   200.1  779.35   209.9  776.56   253.2  773.95   258.9  773.91
   268.2     774   317.8  778.13   366.8  780.13   396.2  780.76   435.4  780.82
   533.5   779.5   592.3  780.61   621.7  781.98   660.9  784.62   700.1  788.53
   719.7  791.18     759  799.06   768.8   800.4   788.4  801.83   798.2  803.79
   837.4  815.16   847.2  818.45     857  822.57     906   846.2  1004.1  884.84
#Mann= 3 , 0 , 0
       0      .1       0   253.2    .045       0   268.2      .1       0
Bank Sta=253.2,268.2
XS Rating Curve= 0 ,0
Exp/Cntr=0.3,0.1

Type RM Length L Ch R = 1 ,9210.3  ,462,471.7,480.3
XS GIS Cut Line= 3
     1545745.934      321850.592      1545524.58      322536.356
     1545407.392      322775.071
#Sta/Elev= 30
       0  854.36   116.8  818.22   126.6  814.26   136.3  808.28   165.5  785.11
   175.3  779.33     185  777.16   194.8  776.66   311.6   773.8   315.1  773.81
   330.1  773.95   399.2  776.43   574.5  780.79     594  781.77   642.7  785.98
   720.6  791.53   730.1  793.69   758.6  803.22   768.1  805.37   806.1  807.64
   815.6  809.56   825.1  812.65   834.6  817.09   844.1  822.57   863.1  834.68
   872.6  839.99   891.6  848.88   929.6  865.42   948.5  874.91   986.5  898.42
#Mann= 3 , 0 , 0
       0      .1       0   315.1    .045       0   330.1      .1       0
Bank Sta=315.1,330.1
XS Rating Curve= 0 ,0
Exp/Cntr=0.3,0.1

Type RM Length L Ch R = 1 ,8738.6  ,369.7,373.3,376.7
XS GIS Cut Line= 4
     1545450.448      321631.379      1545424.63       321801.41
     1545022.991       322257.72      1545051.49      322612.311
#Sta/Elev= 30
       0  860.09    28.7  851.62    47.8  844.69    66.9  836.03   114.6  811.34
   143.3  797.84     172  788.32   191.6  780.51   201.4  777.54   211.2  776.19
   279.8  774.54   404.8  773.53   417.1  773.46   419.8  773.47   495.5  774.28
     721  779.49   740.6   780.6   760.3  782.53   799.1  788.14   827.9  788.46
   837.6  789.67   856.8  794.28   904.9  810.08   943.3  821.45   972.2  831.24
    1001  839.51  1029.8  844.97  1068.3  850.06  1087.5  853.19  1135.6  862.81
#Mann= 3 , 0 , 0
       0      .1       0   404.8    .045       0   419.8      .1       0
Bank Sta=404.8,419.8
XS Rating Curve= 0 ,0
Exp/Cntr=0.3,0.1

Type RM Length L Ch R = 1 ,8365.3  ,678,683.5,688.6
XS GIS Cut Line= 3
     1545263.729      321521.223     1544601.623      322071.739
     1544415.205      322154.903
#Sta/Elev= 30
       0   859.8     9.8  856.21    19.6  851.53    39.1  840.34   107.6  796.43
   127.2  784.76     137  779.75   146.8  776.56   156.6  775.49   195.7  773.13
     225  771.93   293.6  770.73   371.8   770.6   375.8   770.6   390.8  770.61
   401.2  770.81   469.7  774.91   528.4  777.26   665.4   779.4   694.7  781.19
     773  788.16   792.6  789.36   802.4  789.47   841.5   788.3   861.1  789.09
   870.8  791.71   938.8   824.1  1006.9  853.88  1016.6  857.69  1065.2  872.51
#Mann= 3 , 0 , 0
       0      .1       0   375.8    .045       0   390.8      .1       0
Bank Sta=375.8,390.8
XS Rating Curve= 0 ,0
Exp/Cntr=0.3,0.1

Type RM Length L Ch R = 1 ,7681.8  ,1228.6,1221.5,1198.5
XS GIS Cut Line= 3
      1545116.34       321143.98     1544905.837      321114.684
     1544371.983      321402.227
#Sta/Elev= 30
       0  869.55      87   840.2    96.6  836.71   106.3  832.65   193.2  792.53
   212.5  784.39   222.3  781.49   232.1  779.55   241.9  778.17   261.4  776.56
   290.8  775.76   300.6  774.95   310.3  773.19   320.1  769.53   329.9  766.34
   332.5  766.26   339.7  766.02   347.5  766.12     369  766.87   466.8  773.13
   525.5  775.11   642.9  778.23   652.6  778.79   662.4  780.17   672.2   782.5
   711.3  793.16   721.1   795.1   740.7  796.77   750.4  798.23   818.9  814.62
#Mann= 3 , 0 , 0
       0      .1       0   332.5    .045       0   347.5      .1       0
Bank Sta=332.5,347.5
XS Rating Curve= 0 ,0
Exp/Cntr=0.3,0.1

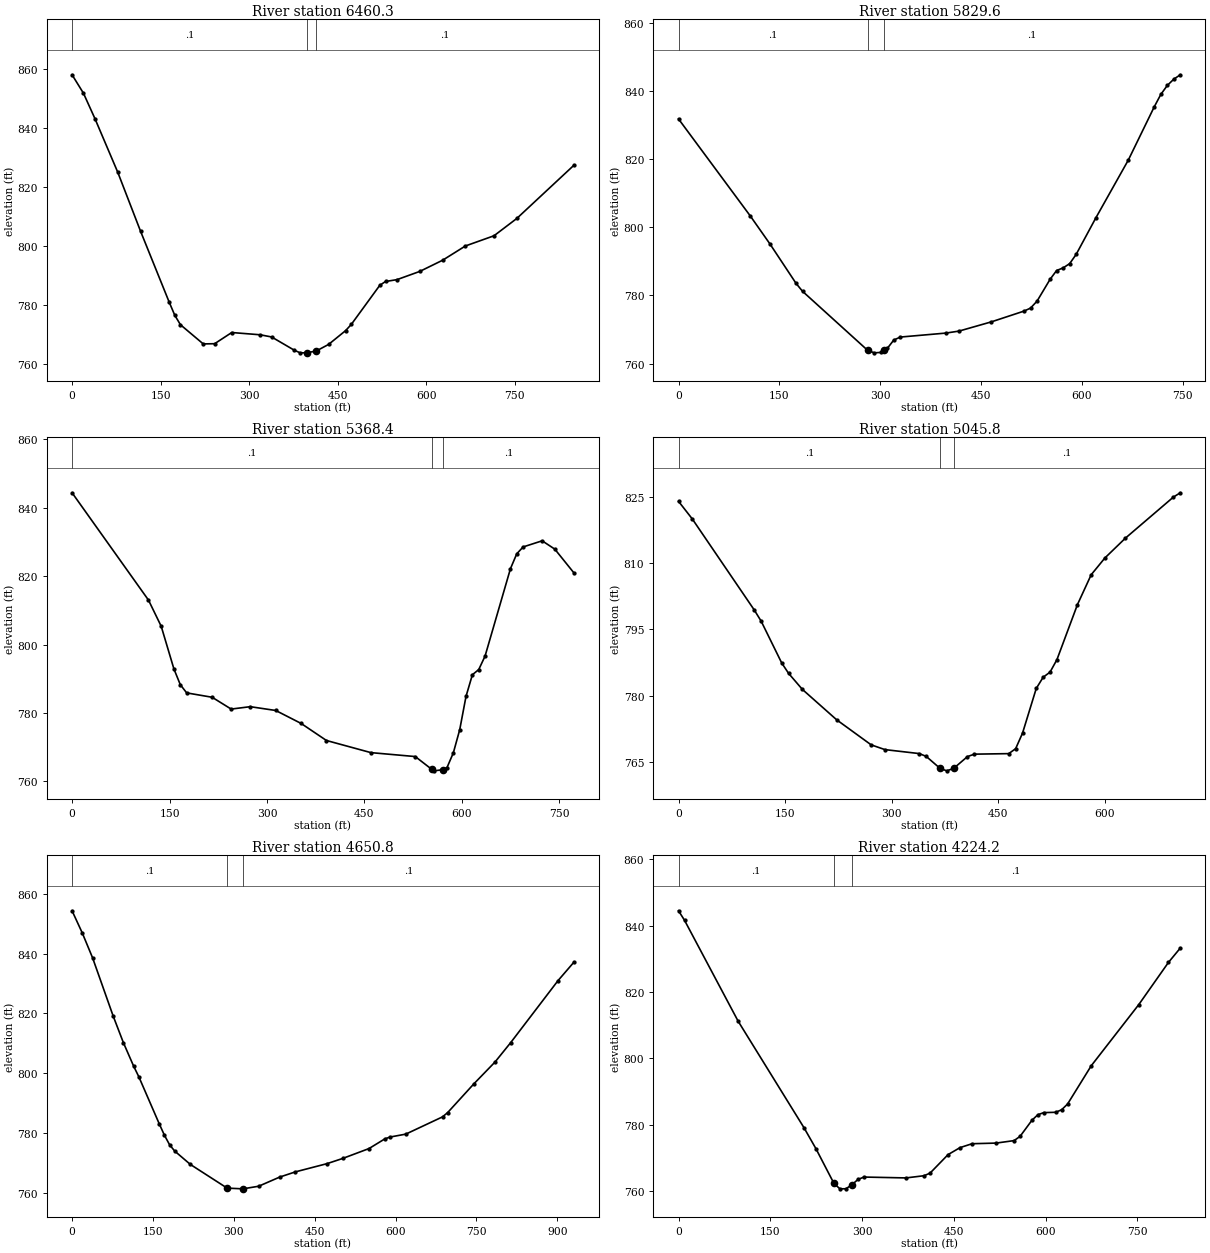
Type RM Length L Ch R = 1 ,6460.3  ,625.3,630.8,635.2
XS GIS Cut Line= 4
     1544532.645       320509.07     1544463.251      320668.612
     1544263.023      320940.518     1544028.088      321183.983
#Sta/Elev= 30
       0  858.11    19.3  851.84    38.7  843.24    77.3  825.06     116  804.99
   164.3  781.01     174  776.44   183.6  773.23   222.2  766.72   241.5  766.79
   270.5  770.59   318.7  769.82     338  769.08   376.6  764.56   386.2  763.71
   395.9  763.69   398.8  763.74   413.8  764.33   434.5  766.54   463.4  771.24
   473.1  773.37   521.3  786.63     531  787.92   550.3  788.54     589  791.34
   627.7  795.14   666.3  799.98   714.7  803.44   753.3  809.31     850  827.37
#Mann= 3 , 0 , 0
       0      .1       0   398.8    .045       0   413.8      .1       0
Bank Sta=398.8,413.8
XS Rating Curve= 0 ,0
Exp/Cntr=0.3,0.1

Type RM Length L Ch R = 1 ,5829.6  ,443.2,461.2,478.3
XS GIS Cut Line= 3
     1544238.722      320264.061     1544051.222      320366.492
     1543721.361      320784.895
#Sta/Elev= 30
       0  831.91   106.8  803.37     136  795.15   174.8  783.57   184.5  781.22
   281.5  763.84   291.2  763.14   300.8  763.26   305.5  763.83   310.5  764.44
   320.2  766.91   329.9  767.78   397.7  768.95   417.1  769.53   465.5  772.26
     514  775.42   523.6   776.3   533.3  778.35   552.7  784.77   562.4  787.35
   572.1  788.12   581.8  789.37   591.4  792.07   620.5  802.74     669  819.81
   707.7  835.51   717.4  839.13   727.1  841.78   736.8  843.63   746.4   844.9
#Mann= 3 , 0 , 0
       0      .1       0   281.5    .045       0   305.5      .1       0
Bank Sta=281.5,305.5
XS Rating Curve= 0 ,0
Exp/Cntr=0.3,0.1

Type RM Length L Ch R = 1 ,5368.4  ,323.4,322.6,321.4
XS GIS Cut Line= 3
     1544223.213      320112.441     1543909.729       320117.36
     1543455.736        320184.2
#Sta/Elev= 30
       0  844.32   117.6  812.98   137.2  805.33   156.8  792.85   166.6  788.27
   176.4  785.87   215.6  784.59   244.9  781.14   274.3  781.84   313.5  780.73
   352.6  776.94   391.6  771.96     460  768.42   528.3  767.27  553.86  763.51
   557.6   763.1  571.05  763.45   577.1  764.04   586.9  768.36   596.7  775.11
   606.4  784.85   616.2  791.17     626  792.69   635.7  796.61   674.8  822.15
   684.5  826.49   694.3   828.5   723.6  830.29   743.1  827.85   772.4  820.94
#Mann= 3 , 0 , 0
       0      .1       0  553.86    .045       0  571.05      .1       0
Bank Sta=553.86,571.05
XS Rating Curve= 0 ,0
Exp/Cntr=0.3,0.1

Type RM Length L Ch R = 1 ,5045.8  ,396.6,395,393.1
XS GIS Cut Line= 3
     1544074.341      319771.491     1543549.601      319861.334
     1543476.685      320018.886
#Sta/Elev= 30
       0     824    19.4     820   106.5  799.39   116.2  796.86   145.2  787.36
   154.9  785.01   174.2  781.39   222.6  774.48     271  768.82   290.4  767.74
   338.8  766.84   348.5   766.2   368.1  763.47   377.5  762.93   387.2   763.5
   406.5  766.16   416.2  766.71   464.6  766.83   474.3  767.95     484  771.48
   503.3   781.6     513  784.14   522.7   785.3   532.4  788.13   561.3  800.62
   580.6  807.37   599.9  811.17   628.8  815.67   696.3  824.97     706  825.94
#Mann= 3 , 0 , 0
       0      .1       0   368.1    .045       0   387.2      .1       0
Bank Sta=368.1,387.2
XS Rating Curve= 0 ,0
Exp/Cntr=0.3,0.1

Type RM Length L Ch R = 1 ,4650.8  ,430.2,426.6,423
XS GIS Cut Line= 3
     1543978.963      319347.445     1543796.672      319429.477
     1543092.245      319623.487
#Sta/Elev= 30
       0  854.32      19  846.87    38.1  838.55    76.2  819.11    95.2  810.18
   114.2  802.33   123.8  798.78   161.8  782.98   171.3  779.21   180.9  776.01
   190.4  773.91   219.4  769.44   287.6  761.52   316.8  761.28     346  762.15
     385  765.21   414.2  766.96   472.7   769.7   501.9  771.45   550.6  774.75
   579.8  777.97   589.6  778.61   618.8  779.58     687  785.36   696.7  786.82
   745.4  796.46   784.4  803.72   813.6  810.24   901.3  830.97   930.6   837.1
#Mann= 3 , 0 , 0
       0      .1       0   287.6    .045       0   316.8      .1       0
Bank Sta=287.6,316.8
XS Rating Curve= 0 ,0
Exp/Cntr=0.3,0.1

Type RM Length L Ch R = 1 ,4224.2  ,503.7,520.8,537.6
XS GIS Cut Line= 4
     1543831.643      319088.825     1543656.216      319091.912
     1543306.763      319248.149     1543045.261      319262.254
#Sta/Elev= 30
       0  844.48     9.8  841.61    97.5  811.19   204.9  779.17   224.5  772.84
     254  762.35   263.8  760.72   273.6  760.74   283.4  761.96   293.2  763.54
     303  764.27   371.8  764.01   401.2  764.67     411  765.44   440.5  771.03
   460.1  773.14   479.7  774.31     519   774.5   548.4  775.25   558.2  776.53
   577.6  781.38   587.3  783.05     597  783.68   616.4  783.78   626.1  784.54
   635.8  786.26   674.6  797.82   752.2  816.22   800.7  828.93   820.1  833.26
#Mann= 3 , 0 , 0
       0      .1       0     254    .045       0   283.4      .1       0
Bank Sta=254,283.4
XS Rating Curve= 0 ,0
Exp/Cntr=0.3,0.1

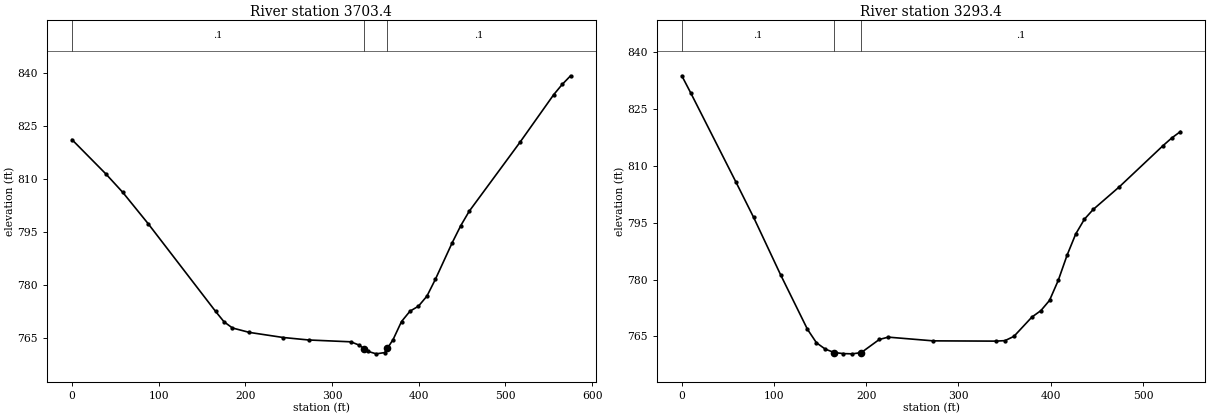
Type RM Length L Ch R = 1 ,3703.4  ,420.2,409.9,399.3
XS GIS Cut Line= 2
     1543766.688      318823.597     1543221.115      318641.305
#Sta/Elev= 30
       0   821.1      39  811.43    58.5  806.22    87.8  797.36   165.7  772.52
   175.5  769.56   185.2  767.82   204.7  766.57   243.7  765.13     273  764.43
   321.7  763.91   331.5  762.96  337.42  761.89   341.2  761.23     351  760.51
   360.7  760.86  363.98   762.1   370.5  764.56   380.2  769.65     390  772.58
   399.7  773.98   409.5  776.83   419.2  781.56   438.7  791.95   448.5  796.74
   458.2  800.81   516.7  820.29   555.7  833.79   565.5  836.69   575.2  839.14
#Mann= 3 , 0 , 0
       0      .1       0  337.42    .045       0  363.98      .1       0
Bank Sta=337.42,363.98
XS Rating Curve= 0 ,0
Exp/Cntr=0.3,0.1

Type RM Length L Ch R = 1 ,3293.4  ,450.8,433.8,417.1
XS GIS Cut Line= 3
       1543794.9      318327.069     1543409.483      318381.757
     1543275.368      318452.069
#Sta/Elev= 30
       0  833.67     9.7  829.14    58.4  805.81    77.9  796.35     107   781.3
   136.2   766.9     146  763.33   155.7  761.64   165.4  760.76   175.2  760.48
   184.9  760.42   194.6  760.75   214.1   764.2   223.8  764.82   272.5  763.84
   340.6  763.77   350.4   763.9   360.1  765.02   379.6  770.11   389.3   771.8
   398.7   774.5   408.2  779.79   417.7  786.38   427.1  791.99   436.6  795.91
   446.1  798.46   474.5  804.44   521.8  815.27   531.2  817.28   540.7  818.98
#Mann= 3 , 0 , 0
       0      .1       0   165.4    .045       0   194.6      .1       0
Bank Sta=165.4,194.6
XS Rating Curve= 0 ,0
Exp/Cntr=0.3,0.1