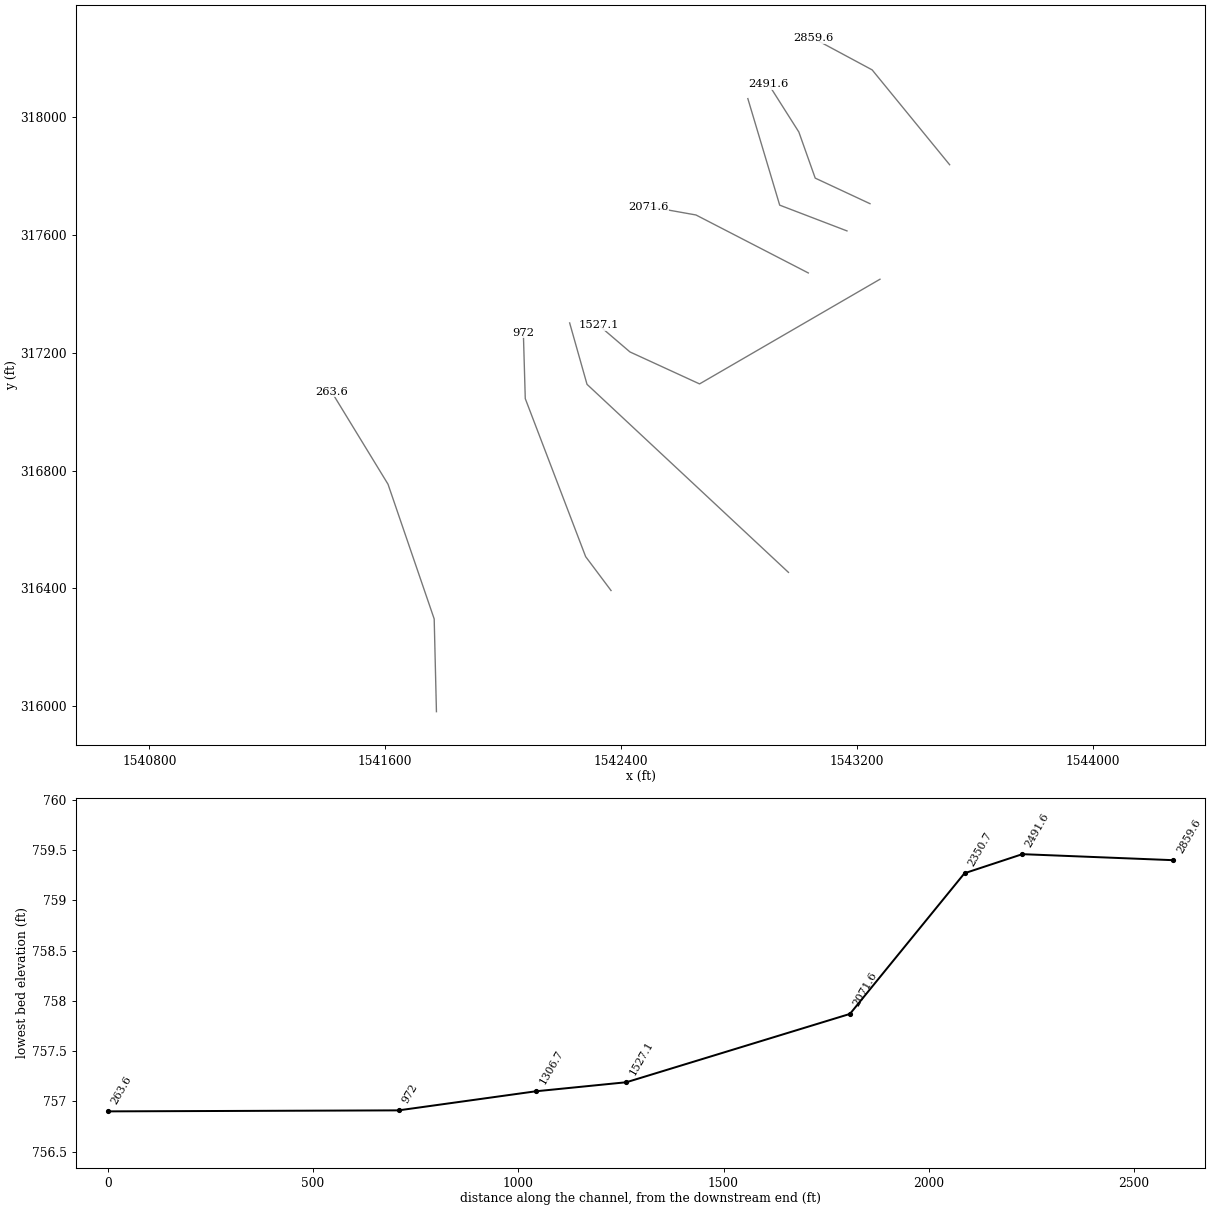
HEC-RAS study MCKIMCRK.prj: MCKIMCRK

--- MCKIMCRK.g04 (geometry) --- (continued)

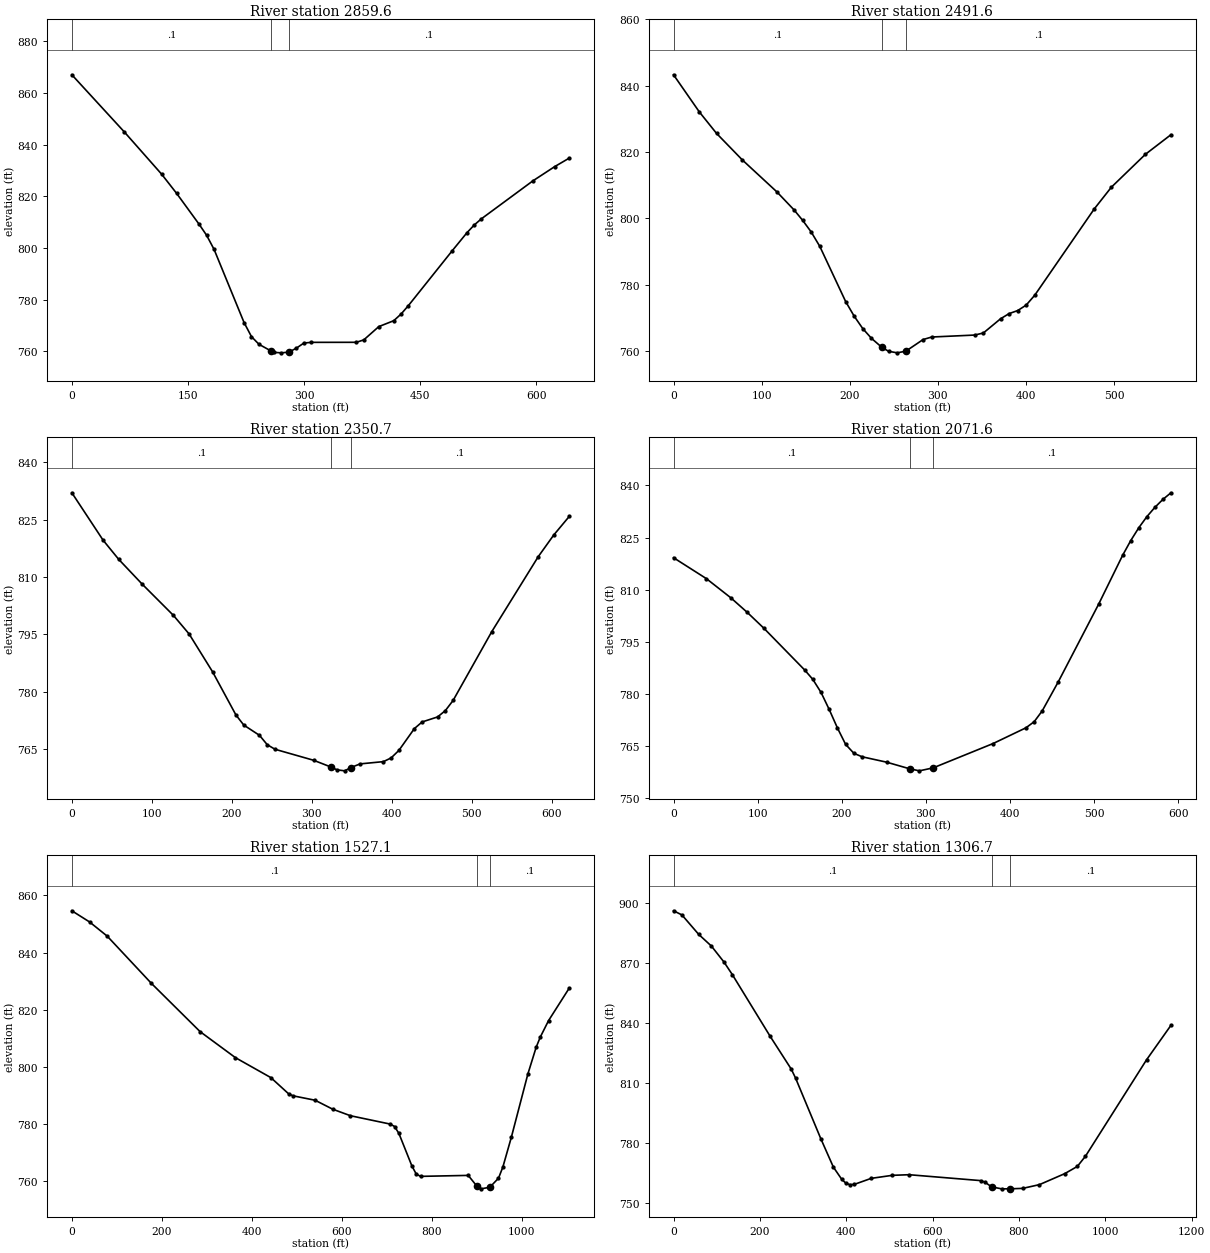
Type RM Length L Ch R = 1 ,2859.6  ,375.7,368.1,360.1
XS GIS Cut Line= 3
      1543513.65      317838.788     1543250.914      318160.917
     1543051.261      318268.339
#Sta/Elev= 30
       0  867.07    67.7  844.96     116  828.56   135.3  821.15   164.3  809.21
     174  804.94   183.7  799.44   222.4  771.13     232  765.66   241.7   762.7
   257.8  760.02     261  759.58   270.7   759.4   280.4  759.68     290  761.22
   299.7   763.2   309.4  763.46   367.4  763.48     377  764.41   396.4  769.56
   415.7  771.84   425.1   774.4   434.6  777.68   491.3  798.96   510.2  805.89
   519.6  808.89     529  811.32   595.2  825.95   623.5   831.5   642.4  834.81
#Mann= 3 , 0 , 0
       0      .1       0   257.8    .045       0   280.4      .1       0
Bank Sta=257.8,280.4
XS Rating Curve= 0 ,0
Exp/Cntr=0.3,0.1

Type RM Length L Ch R = 1 ,2491.6  ,142,140.9,139.7
XS GIS Cut Line= 4
     1543243.622       317706.49     1543057.858      317793.296
     1543002.386      317949.856     1542899.001      318113.137
#Sta/Elev= 30
       0  843.26    29.3  832.06    48.8   825.6    78.1  817.59   117.2  807.99
   136.7  802.55   146.5   799.4   156.2  795.89     166  791.53   195.3  774.92
     205   770.5   214.8  766.74   224.6  763.83  236.54761.0807   244.1  759.92
   253.9  759.46   263.7  759.98   283.2  763.47     293  764.23   341.8  764.82
   351.6  765.45   371.1  769.73   380.8  771.29   390.5   772.2   400.1  773.84
   409.8   776.8   477.4  802.84   496.8  809.38   535.4  819.29   564.4   825.2
#Mann= 3 , 0 , 0
       0      .1       0  236.54    .045       0   263.7      .1       0
Bank Sta=236.54,263.7
XS Rating Curve= 0 ,0
Exp/Cntr=0.3,0.1

Type RM Length L Ch R = 1 ,2350.7  ,262.1,279.1,296.8
XS GIS Cut Line= 3
     1543165.549      317614.001     1542937.424      317701.501
     1542829.421      318063.341
#Sta/Elev= 30
       0  832.07    39.1  819.65    58.6  814.64      88  808.14     127  799.97
   146.6  795.11   175.9  785.22   205.2  773.89     215  771.25   234.6  768.57
   244.3  766.12     254  764.92   302.4  762.03  324.27760.2455   331.5  759.53
   341.2  759.27   348.5   760.1   360.5  761.09   389.6  761.68   399.2  762.65
   408.9  764.61   428.3  770.33     438  772.07   457.3  773.38     467  775.03
   476.7  777.69   525.1  795.72   583.2  815.35   602.6  821.02     622  825.89
#Mann= 3 , 0 , 0
       0      .1       0  324.27    .045       0   348.5      .1       0
Bank Sta=324.27,348.5
XS Rating Curve= 0 ,0
Exp/Cntr=0.3,0.1

Type RM Length L Ch R = 1 ,2071.6  ,541.7,544.5,546
XS GIS Cut Line= 3
     1543034.418       317471.21     1542653.553      317668.115
     1542493.397      317696.761
#Sta/Elev= 30
       0  819.19      39  813.18    68.2  807.64    87.7  803.45   107.2  798.95
   155.9  786.89   165.6  784.19   175.4  780.42   185.1  775.52   194.9  770.19
   204.6  765.49   214.4  762.92   224.1  761.92   253.4  760.36   280.6758.4669
   292.3  757.87  308.77 758.732     380  765.73     419  770.25   428.8  772.01
   438.3   775.1   457.5  783.51   505.3  805.76     534   819.9   543.6  824.12
   553.2  827.82   562.7  830.98   572.3  833.68   581.9  835.98   591.4  837.87
#Mann= 3 , 0 , 0
       0      .1       0   280.6    .045       0  308.77      .1       0
Bank Sta=280.6,308.77
XS Rating Curve= 0 ,0
Exp/Cntr=0.3,0.1

Type RM Length L Ch R = 1 ,1527.1  ,228.9,220.4,210.5
XS GIS Cut Line= 4
     1543277.471      317449.862     1542665.706      317094.331
     1542429.687      317202.937     1542324.913      317292.738
#Sta/Elev= 30
       0  854.63    39.3  850.72    78.6  845.74   176.9  829.17     285  812.28
   363.6  803.15   442.2  796.17   481.5  790.52   491.4  789.79   540.5  788.24
   579.8  785.09   619.1  782.81   707.6  779.88   717.2  779.03   726.8   776.6
   755.7  765.19   765.3  762.38   774.9  761.56   880.8   761.9     900  758.15
   909.6  757.19   928.9  757.76   948.1  760.92   957.8  764.82   976.6  775.23
  1013.4  797.45  1031.8   806.8    1041  810.38  1059.4  816.16  1105.4  827.55
#Mann= 3 , 0 , 0
       0      .1       0     900    .045       0   928.9      .1       0
Bank Sta=900,928.9
XS Rating Curve= 0 ,0
Exp/Cntr=0.3,0.1

Type RM Length L Ch R = 1 ,1306.7  ,343.4,334.7,326.4
XS GIS Cut Line= 3
     1542967.141      316454.203     1542284.114      317092.894
     1542225.231      317301.499
#Sta/Elev= 30
       0  895.89    19.5  893.81    58.4  884.09    87.7  878.28   116.9  870.29
   136.4  863.96     224  833.15   272.7  816.83   282.5  812.44   340.9  782.21
   370.2  767.93   389.6  761.84   399.4  759.86   409.1  759.14   418.9  759.35
   457.8  762.33   506.5  763.84   545.5  764.15   711.1  761.21   720.8  760.47
  736.58758.0846   759.8   757.1   779.3  757.11   808.5  757.33   847.4   759.2
   905.9  764.68   935.1  768.29     954   773.4  1095.3  821.48  1151.9  838.72
#Mann= 3 , 0 , 0
       0      .1       0  736.58    .045       0   779.3      .1       0
Bank Sta=736.58,779.3
XS Rating Curve= 0 ,0
Exp/Cntr=0.3,0.1

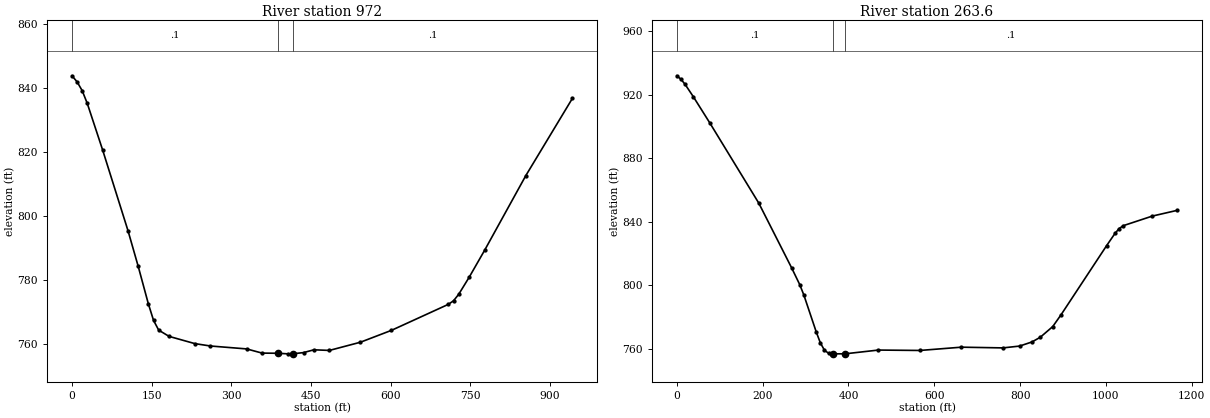
Type RM Length L Ch R = 1 ,972     ,704.8,708.4,709.8
XS GIS Cut Line= 4
     1542365.578      316392.571     1542279.484      316507.662
     1542074.768      317044.409     1542068.257      317267.934
#Sta/Elev= 30
       0  843.84     9.6  841.94    19.2  839.18    28.8  835.18    57.5  820.73
   105.4  795.42   124.6  784.28   143.7  772.56   153.5  767.37   163.2  764.32
   182.7  762.37   231.4   760.1   260.6  759.36   328.7  758.45   357.9  757.14
   387.2  757.09   406.6  756.91   416.4  756.94   435.8   757.3   455.3  758.17
   484.5  757.98   542.9  760.54   601.4  764.26   708.4  772.38   718.2  773.51
   727.9  775.52   747.4   780.8   776.5  789.23   854.3  812.65   941.8  836.74
#Mann= 3 , 0 , 0
       0      .1       0   387.2    .045       0   416.4      .1       0
Bank Sta=387.2,416.4
XS Rating Curve= 0 ,0
Exp/Cntr=0.3,0.1

Type RM Length L Ch R = 1 ,263.6   ,273.2,263.6,253.5
XS GIS Cut Line= 4
     1541773.564      315981.112     1541765.926      316296.043
     1541609.387      316753.664      1541417.98      317067.466
#Sta/Elev= 30
       0  931.88     9.6  929.67    19.1  926.52    38.2  918.77    76.4  902.38
   190.9  851.76   267.3  811.11   286.4  800.46   295.9  793.98   324.7  770.81
   334.4  763.83     344  759.18   353.7  757.25   363.4   756.9   392.4  756.93
   469.8  759.28   566.5  759.03   663.2  761.09     760  760.64   798.7  761.78
   827.7  764.38     847  767.33   876.1  774.06   895.4  781.46  1001.8  825.05
  1021.2  832.67  1030.8  835.73  1040.5  837.55  1108.2  843.59  1166.2   847.2
#Mann= 3 , 0 , 0
       0      .1       0   363.4    .045       0   392.4      .1       0
Bank Sta=363.4,392.4
XS Rating Curve= 0 ,0
Exp/Cntr=0.3,0.1